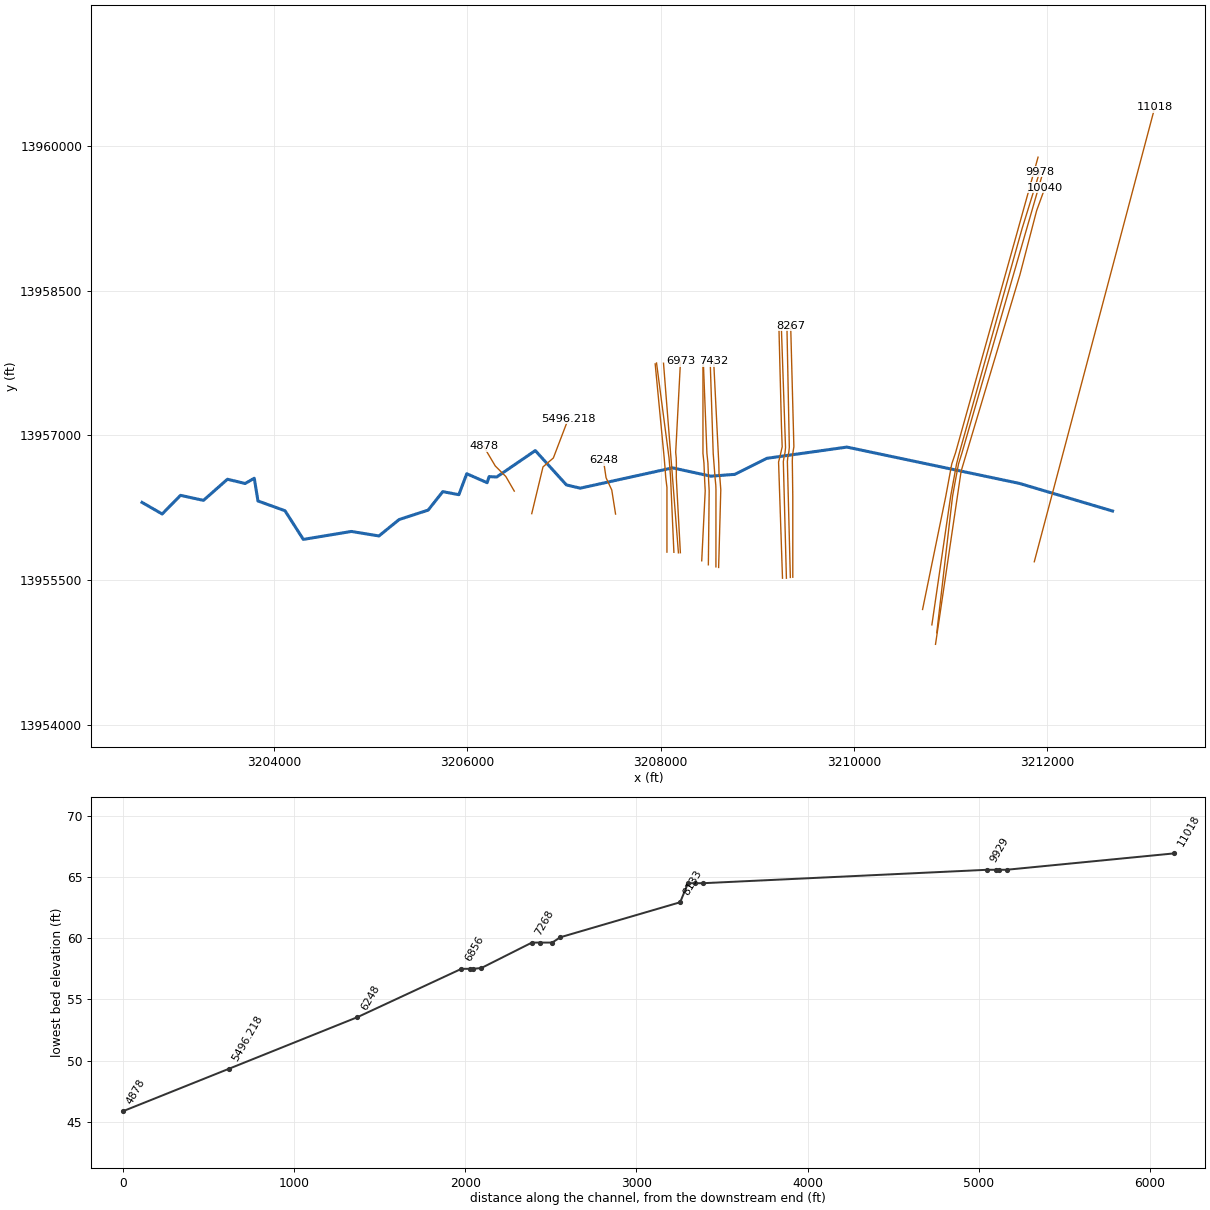
--- S110-00-00.prj (project) ---

Proj Title=S110-00-00
Current Plan=p02
Default Exp/Contr=.3,.1
English Units
Geom File=g02
Flow File=f02
Flow File=f01
Plan File=p01
Plan File=p02
Y Axis Title=Elevation
X Axis Title(PF)=Main Channel Distance
X Axis Title(XS)=Station
BEGIN DESCRIPTION:
Luce Bayou Watershed
Shook Gully
HCFCD unit S110-00-00
(Flood Hazard, Floodway)Model
10, 2, 1, 0.2% Event
Filename S1100000.prj
Prepared by:  FTN Associates Ltd.   DATE:  February 2003
Reviewed by: 	 DATE:
STATUS (Final)
Slope Boundary Condition: The slope boundary condition was determined using river                                                      stations 1937 and 3259.  A slope of 0.0030 was calculated.
END DESCRIPTION:
DSS Export Rating Curves= 0
DSS Export Rating Curve Sorted= 0
DSS Export Volume Flow Curves= 0
DXF OffsetX= 0
DXF OffsetY= 0
DXF ScaleX= 1
DXF ScaleY= 10

--- S110-00-00.p02 (plan) ---

Plan Title=Floodway
Version=Version 3.0.1  Mar 2001
Short Identifier=Floodway0607
Geom File=g02
Flow File=f02
Subcritical Flow
K Sum by GR= 0
Std Step Tol= 0.01
Critical Tol= 0.01
Num of Std Step Trials= 20
Max Error Tol= 0.3
Flow Tol Ratio= 0.001
Split Flow NTrial= 30
Split Flow Tol= 0.02
Split Flow Ratio= 0.02
Log Output Level= 0
Friction Slope Method= 1
Unsteady Friction Slope Method= 2
Parabolic Critical Depth
Global Vel Dist= 0 , 0 , 0
Global Log Level= 0
CheckData=True
Encroach Param=-1 ,0,0, 2
Encroach River=S110-00-00
Encroach Reach=Shook Gully
Encroach Node=11018
       1     400    1800
Encroach Node=10040
       1     803    1004
Encroach Node=9998
       1     928    1145
Encroach Node=9988
       1     928    1145
Encroach Node=9978
       1     985    1203
Encroach Node=9929
       1    1145    1338
Encroach Node=8267
       1     407     551
Encroach Node=8220
       1     406     543
Encroach Node=8200
       1     406     543
Encroach Node=8180
       1     400     527
Encroach Node=8133
       1     383     504
Encroach Node=7432
       1     249     299
Encroach Node=7387
       1     229     279
Encroach Node=7351
       1     225     279
Encroach Node=7316
       1     225     276
Encroach Node=7268
       1     208     258
Encroach Node=6973
       1     197     302
Encroach Node=6926
       1     187     292
Encroach Node=6916
       1     185     292
Encroach Node=6906
       1     185     290
Encroach Node=6856
       1     176     281
Encroach Node=6248
       1  246.49     365
Encroach Node=5496.218
       1  559.74  638.74
Encroach Node=4878
       1     225  289.54
Encroach Node=3726
       1     186  292.42
Encroach Node=3680
       1  169.47  297.83
Encroach Node=3672
       1  163.63  287.52
Encroach Node=3664
       1  163.63  287.52
Encroach Node=3625
       1  174.35  275.29
Encroach Node=3259
       1     466  561.13
Encroach Node=3209
       1     453  552.94
Encroach Node=3168
       1     453  562.91
Encroach Node=3127
       1     463  562.91
Encroach Node=3071
       1     477  600.04
Encroach Node=1937
       1     659     779
Encroach Node=578
       1    1222    1554
Encroach Reach=S110-00-00_0006
Encroach Node=11018
       1     400    1800
Encroach Node=10040
       1     803    1004
Encroach Node=9998
       1     928    1145
Encroach Node=9988
       1     928    1145
Encroach Node=9978
       1     985    1203
Encroach Node=9929
       1    1145    1338
Encroach Node=8267
       1     407     551
Encroach Node=8220
       1     406     543
Encroach Node=8200
       1     406     543
Encroach Node=8180
       1     400     527
Encroach Node=8133
       1     383     504
Encroach Node=7432
       1     249     299
Encroach Node=7387
       1     229     279
Encroach Node=7351
       1     225     279
Encroach Node=7316
       1     225     276
Encroach Node=7268
       1     208     258
Encroach Node=6973
       1     197     302
Encroach Node=6926
       1     187     292
Encroach Node=6916
       1     185     292
Encroach Node=6906
       1     185     290
Encroach Node=6856
       1     176     281
Encroach Node=6248
       1  246.49     365
Encroach Node=5496.218
       1  559.74  638.74
Encroach Node=4878
       1     225  289.54
Encroach Node=3726
       1     186  292.42
Encroach Node=3680
       1  169.47  297.83
Encroach Node=3672
       1  163.63  287.52
Encroach Node=3664
       1  163.63  287.52
Encroach Node=3625
       1  174.35  275.29
Encroach Node=3259
       1     466  561.13
Encroach Node=3209
       1     453  552.94
Encroach Node=3168
       1     453  562.91
Encroach Node=3127
       1     463  562.91
Encroach Node=3071
       1     477  600.04
Encroach Node=1937
       1     659     779
Encroach Node=578
       1    1222    1554
Computation Interval=1HOUR
Output Interval=1HOUR
Run HTab= 0
Run UNet= 0
Run PostProcess= 0
UNET Theta= 1
UNET ZTol= 0.02
UNET ZSATol= 0.1
UNET MxIter= 20
UNET MaxInSteps= 20
UNET DtIC= 0
UNET DtMin= 0
UNET MaxCRTS= 20
UNET WFStab= 2
UNET SFStab= 1
UNET WFX= 1
UNET SFX= 1
UNET Convert EG Bridges=-1
UNET Use Existing IB Tables=-1
Instantaneous Interval=1HOUR
Write IC File= 0
Write Velocity= 0
Write Detailed= 0

--- S110-00-00.p01 (plan) ---

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Plan Title=FEMA Effective June 2007
Short Identifier=FEMAeff0607
Geom File=g02
Flow File=f01
IC Time=0

--- S110-00-00.f02 (steady flow) ---

Flow Title=Floodway
Version=Version 3.0.1  Mar 2001
Number of Profiles= 2
Profile Names=1PCT_100yr,1PCTFloodway_100yrFW
River Rch & RM=S110-00-00,S110-00-00_0006 ,11018
    1158    1158
River Rch & RM=S110-00-00,S110-00-00_0006 ,10040
    1151    1151
River Rch & RM=S110-00-00,S110-00-00_0006 ,9929
    1248    1248
River Rch & RM=S110-00-00,S110-00-00_0006 ,8267
    1299    1299
River Rch & RM=S110-00-00,S110-00-00_0006 ,7432
    1336    1336
River Rch & RM=S110-00-00,S110-00-00_0006 ,6856
    1375    1375
River Rch & RM=S110-00-00,S110-00-00_0006 ,6248
    1470    1470
River Rch & RM=S110-00-00,S110-00-00_0006 ,4878
    1554    1554
River Rch & RM=S110-00-00,S110-00-00_0006 ,3726
    1604    1604
River Rch & RM=S110-00-00,S110-00-00_0006 ,3071
    1694    1694
River Rch & RM=S110-00-00,S110-00-00_0006 ,1937
    1809    1809
River Rch & RM=S110-00-00,S110-00-00_0006 ,578
    1860    1860
Boundary for River Rch & Prof#=S110-00-00,S110-00-00_0006 , 1
Up Type= 0
Dn Type= 3
Dn Slope=.003
Boundary for River Rch & Prof#=S110-00-00,S110-00-00_0006 , 2
Up Type= 0
Dn Type= 3
Dn Slope=.003
DSS Import GetInterval= 0
DSS Import GetPeak= 0
DSS Import FillOption= 0

--- S110-00-00.f01 (steady flow) ---

Flow Title=FEMA Effective June 2007
Version=Version 3.0.1  Mar 2001
Number of Profiles= 4
Profile Names=10PCT_10yr,2PCT_50yr,1PCT_100yr,0.2PCT_500yr
River Rch & RM=S110-00-00,S110-00-00_0006 ,11018
     653     987    1158    1657
River Rch & RM=S110-00-00,S110-00-00_0006 ,10040
     656     992    1151    1372
River Rch & RM=S110-00-00,S110-00-00_0006 ,9929
     710    1073    1248    1512
River Rch & RM=S110-00-00,S110-00-00_0006 ,8267
     739    1117    1299    1588
River Rch & RM=S110-00-00,S110-00-00_0006 ,7432
     759    1148    1336    1643
River Rch & RM=S110-00-00,S110-00-00_0006 ,6856
     781    1181    1375    1702
River Rch & RM=S110-00-00,S110-00-00_0006 ,6248
     833    1260    1470    1844
River Rch & RM=S110-00-00,S110-00-00_0006 ,4878
     880    1331    1554    1973
River Rch & RM=S110-00-00,S110-00-00_0006 ,3726
     908    1373    1604    2050
River Rch & RM=S110-00-00,S110-00-00_0006 ,3071
     958    1449    1694    2191
River Rch & RM=S110-00-00,S110-00-00_0006 ,1937
    1022    1545    1809    2373
River Rch & RM=S110-00-00,S110-00-00_0006 ,578
    1050    1588    1860    2454
Boundary for River Rch & Prof#=S110-00-00,S110-00-00_0006 , 1
Up Type= 0
Dn Type= 3
Dn Slope=.003
Boundary for River Rch & Prof#=S110-00-00,S110-00-00_0006 , 2
Up Type= 0
Dn Type= 3
Dn Slope=.003
Boundary for River Rch & Prof#=S110-00-00,S110-00-00_0006 , 3
Up Type= 0
Dn Type= 3
Dn Slope=.003
Boundary for River Rch & Prof#=S110-00-00,S110-00-00_0006 , 4
Up Type= 0
Dn Type= 3
Dn Slope=.003
DSS Import GetInterval= 0
DSS Import GetPeak= 0
DSS Import FillOption= 0

--- S110-00-00.g02 (geometry) ---

Geom Title=S110-00-00 June 2007
Version=Version 3.0.1  Mar 2001

River Reach=S110-00-00      ,S110-00-00_0006
Reach XY= 30
     3212675.459    13956217.936     3211712.556    13956503.798
     3209927.173    13956879.932     3209098.938    13956763.783
     3208766.511     13956597.57     3208518.242    13956578.634
     3208122.696    13956664.897     3207167.494      13956454.5
     3207024.424    13956488.163     3206702.517    13956843.734
     3206302.763    13956570.218     3206224.916    13956574.426
     3206203.877    13956511.307      3205993.48    13956603.882
     3205911.425    13956387.173     3205745.212    13956418.732
     3205593.726    13956227.271     3205294.962    13956130.489
     3205084.565    13955960.067     3204798.426    13956006.355
     3204301.889      13955924.3     3204112.532    13956220.959
     3203832.704     13956321.95     3203794.833    13956557.594
     3203700.154    13956502.891     3203517.109    13956547.074
      3203268.84    13956328.262     3203031.223    13956380.192
     3202841.735    13956187.296     3202633.442    13956307.222

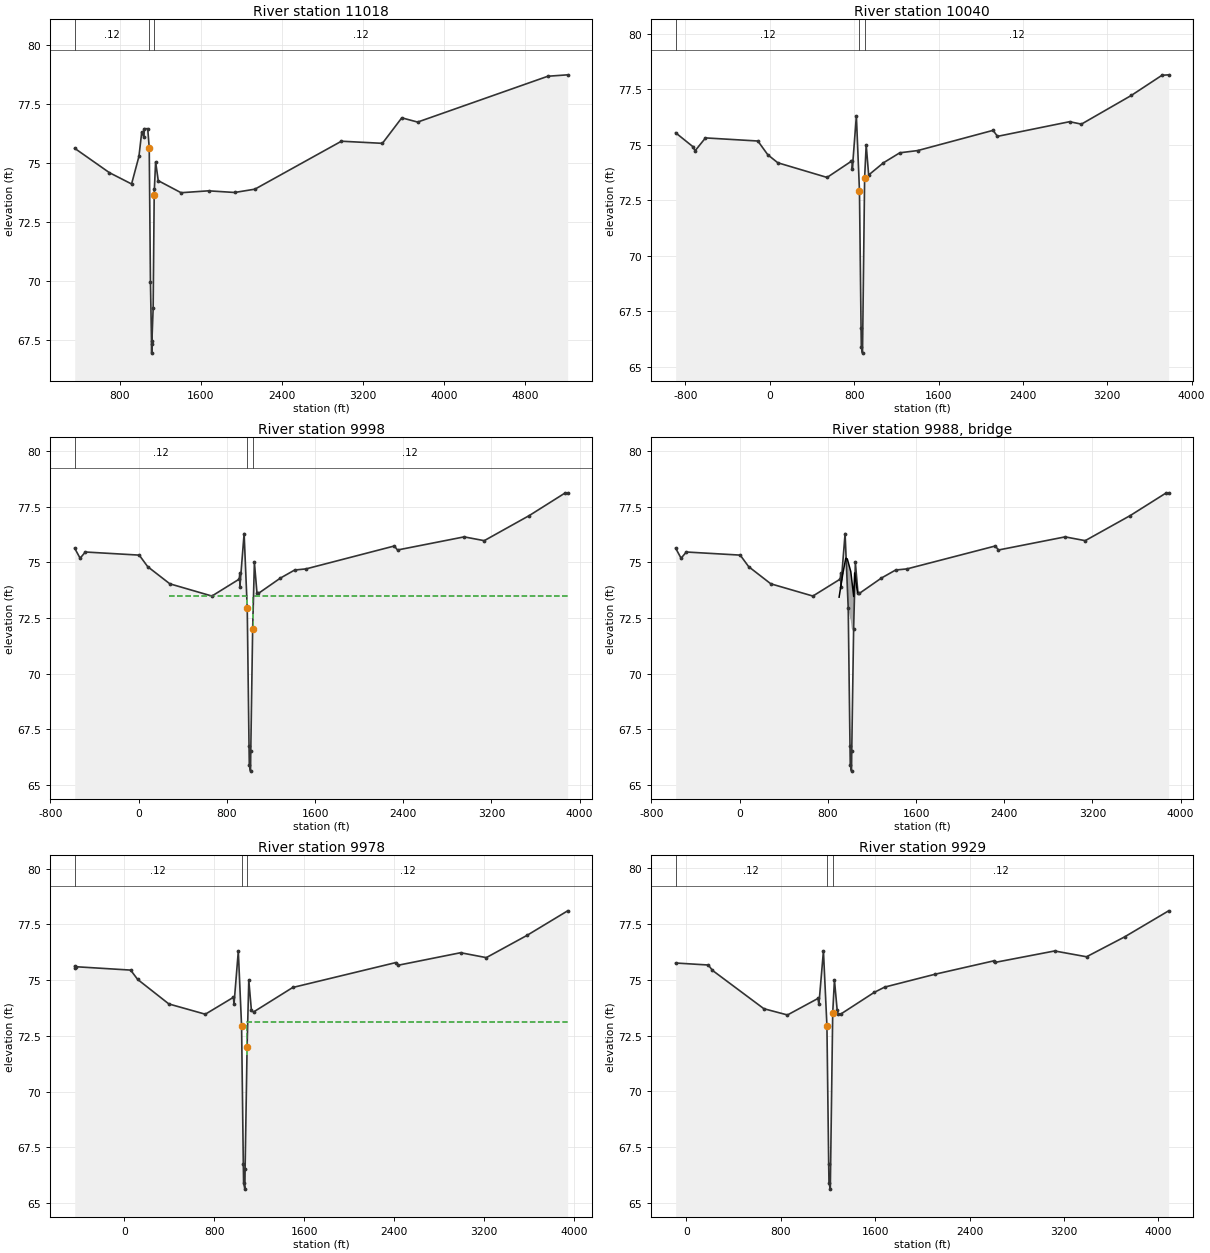
Type RM Length L Ch R = 1 ,11018   ,963,978,964
BEGIN DESCRIPTION:
483v1
Lateral weir added from 11018 to 9091 to allow overflows out of watershed due to water surface elevations exceeding high ground elevations of LOB.  DEC then recomputed flood flows.
Bank Station Offset = -1030
END DESCRIPTION:
XS GIS Cut Line= 4
 3211865.773184313955692.8508037 3212129.637943713956688.4789099
     3212779.332    13959139.938 3213112.565028813960397.3100345
#Sta/Elev= 28
  353.09   75.63  695.29    74.6  914.72   74.12  987.55   75.29 1015.13   76.32
 1037.46   76.09    1039   76.46    1074   76.46    1089   75.66    1101   69.96
  1111.5   67.47    1113   66.96  1114.5   67.36  1127.7   68.86    1138   73.66
    1140   73.92    1152   75.06    1178   74.26 1403.31   73.75 1674.63   73.83
 1932.54   73.76 2132.17    73.9 2986.32   75.93 3391.07   75.84 3582.34   76.92
 3738.91   76.74 5024.28   78.68 5219.96   78.74
#Mann= 3 ,-1 , 0
  353.09     .12       0    1089     .06       0    1138     .12       0
Bank Sta=1089,1138
XS Rating Curve= 0
Exp/Cntr=.3,.1

Type RM Length L Ch R = 1 ,10040   ,50,43,48
BEGIN DESCRIPTION:
483s6u, xs 4/4 "Conc Bridge" unnamed
Lateral weir added from 11018 to 9091 to allow overflows out of watershed due to water surface elevations exceeding high ground elevations of LOB.  DEC then recomputed flood flows.
Bank Station Offset = -1090
Adjusted contraction coefficient to 0.3 and expansion coefficient to 0.5.
END DESCRIPTION:
XS GIS Cut Line= 6
 3210843.669743513954837.7357097     3211105.685    13956610.384
     3211116.287    13956655.819     3211716.866    13958663.606
     3211889.934    13959327.907   3211975.6830413959563.7186995
#Sta/Elev= 29
 -892.83   75.54 -730.52   74.92 -708.69   74.73 -610.21   75.31 -113.22   75.17
     -19   74.55   75.91   74.19  542.92   73.53  773.39   74.26   781.8   74.26
   782.3   73.91  820.68    76.3     850   72.94  865.22   66.73  867.63   65.91
  878.86   65.62     899   73.52  913.89      75  937.16   73.64 1077.56   74.19
  1232.8   74.64 1402.27   74.74 2116.73   75.65  2158.9   75.38 2842.61   76.04
 2954.51   75.93 3427.09   77.22 3718.53   78.13 3781.64   78.15
#Mann= 3 ,-1 , 0
 -892.83     .12       0     850     .06       0     899     .12       0
Bank Sta=850,899
XS Rating Curve= 0
Exp/Cntr=.5,.3

Type RM Length L Ch R = 1 ,9998    ,19,20,27
BEGIN DESCRIPTION:
copy of 483s6u, xs 3/4 "Conc Bridge" unnamed
Lateral weir added from 11018 to 9091 to allow overflows out of watershed due to water surface elevations exceeding high ground elevations of LOB.  DEC then recomputed flood flows.
Bank Station Offset = -965
Used x-sec sta 1979.82 for station equation. Adjusted contraction coefficient to 0.3 and expansion coefficient to 0.5. No elevation change b/c no invert data from survey. Right CB elev. was lowered from 73.52' to 72' to show deck.
END DESCRIPTION:
XS GIS Cut Line= 6
 3210856.686601913954957.3979123     3211019.997    13956370.762
     3211049.921    13956536.394      3211081.98    13956705.917
     3211116.334    13956815.935 3211941.834498813959676.4223767
#Sta/Elev= 30
 -580.03   75.64 -530.78   75.19 -483.58   75.47    5.44   75.33   82.32   74.81
  282.92   74.04  664.49   73.49  911.89   74.25  917.87   74.51  918.26   73.91
  956.64    76.3     985   72.94 1001.18   66.73 1003.59   65.91 1014.82   65.62
 1017.06   66.53    1034      72 1049.85      75 1073.12   73.64 1086.42   73.61
 1286.44    74.3 1415.12   74.66  1517.6   74.71 2318.86   75.74 2347.79   75.56
 2952.17   76.15 3134.48   75.98 3543.56   77.11 3866.82   78.12 3891.09   78.13
#Mann= 3 ,-1 , 0
 -580.03     .12       0     985     .06       0    1034     .12       0
#XS Ineff= 2 , 0
  277.48  983.48   73.47 1034.48  277.48   73.47
Permanent Ineff=
       F       F
Bank Sta=985,1034
XS Rating Curve= 0
Exp/Cntr=.5,.3

Type RM Length L Ch R = 3 ,9988    ,,,
BEGIN DESCRIPTION:
483s6: Unnamed Road (Length 58')
Right Cb elev. was lowered @ both upstream and downstream bounding sections to show deck.
END DESCRIPTION:
Bridge Culvert--1,0,-1,-1, 0
Deck Dist Width WeirC Skew NumUp NumDn MinLoCord MaxHiCord MaxSubmerge Is_Ogee
5,10,2.6,0, 8, 8, 73.44, , .95, 0, 0,0,,
  902.41  937.18  962.93  976.66 1008.26 1034.76 1043.44 1069.32
   73.44   74.53   75.19   75.16   74.59   73.47   74.53   73.65
       0       0       0   72.96   72.39   71.27       0       0
  956.71  991.48 1017.23 1030.96 1062.56 1089.06 1097.74 1123.62
   73.44   74.53   75.19   75.16   74.59   73.47   74.53   73.65
       0       0       0   72.96   72.39   71.27       0       0
BR Coef=-1 , 0 , 0 ,, 0 ,,,.8,0,,0,
WSPro=,,,, 1 ,,,, 0 ,,,, 0 ,,,,-1 ,-1 ,-1 , 0 , 0 , 0 , 0 , 0
BC Design=,, 0 ,, 0 ,,,,,,

Type RM Length L Ch R = 1 ,9978    ,50,49,39
BEGIN DESCRIPTION:
copy of 483s6u, xs 2/4 "Conc Bridge" unnamed
Lateral weir added from 11018 to 9091 to allow overflows out of watershed due to water surface elevations exceeding high ground elevations of LOB.  DEC then recomputed flood flows.
Bank Station Offset = -890
Adjusted contraction coefficient to 0.3 and expansion coefficient to 0.5. No elevation change b/c no invert data from survey. Right CB elev. was lowered from 73.52' to 72' to show deck.
END DESCRIPTION:
XS GIS Cut Line= 6
 3210806.091229613955039.0462698     3211000.497    13956370.762
     3211061.031    13956703.902     3211086.056    13956804.004
     3211739.308    13959141.819 3211922.0384818 13959731.299165
#Sta/Elev= 26
 -440.81   75.62 -433.65   75.55  -426.5    75.6   56.57   75.45  119.34   75.03
  396.66   73.93  720.49   73.47  970.91   74.23  975.53   73.91 1013.91    76.3
    1043   72.94 1058.45   66.73 1060.86   65.91 1072.09   65.62 1074.33   66.53
    1092      72 1107.12      75 1130.39   73.64 1149.15   73.57  1497.8   74.67
 2416.27   75.79 2436.68   75.67 2990.39   76.23 3218.81   76.01 3581.32   77.01
 3942.13   78.11
#Mann= 3 ,-1 , 0
 -440.81     .12       0    1043     .06       0    1092     .12       0
#XS Ineff= 2 , 0
    -890 1040.78   73.13 1090.78    -890   73.13
Permanent Ineff=
       F       F
Bank Sta=1043,1092
XS Rating Curve= 0
Exp/Cntr=.5,.3

Type RM Length L Ch R = 1 ,9929    ,1669,1662,1742
BEGIN DESCRIPTION:
copy of 483s6u, xs 1/4 "Conc Bridge" unnamed
Lateral weir added from 11018 to 9091 to allow overflows out of watershed due to water surface elevations exceeding high ground elevations of LOB.  DEC then recomputed flood flows.
Bank Station Offset = -750
No elevation change b/c no invert data from survey.
The difference in length of ROB is greater than 20' with respect to main channel length.
END DESCRIPTION:
XS GIS Cut Line= 6
 3210709.745727513955198.5184095     3210949.997    13956370.762
      3211011.98    13956705.917     3211050.658     13956820.05
     3211687.018    13959097.227 3211904.697188313959881.7539309
#Sta/Elev= 26
  -90.84   75.76  185.93   75.67  220.83   75.43  656.83   73.71  856.51   73.43
 1114.76   74.17 1123.01   73.91 1161.39    76.3    1191   72.94 1205.93   66.73
 1208.34   65.91 1219.57   65.62    1240   73.52  1254.6      75 1277.87   73.64
  1284.6   73.47 1308.17   73.47 1590.99   74.44 1680.44   74.68 2109.92   75.26
 2607.42   75.86 2618.39   75.79 3120.33    76.3 3391.14   76.04 3712.91   76.93
 4086.55    78.1
#Mann= 3 ,-1 , 0
  -90.84     .12       0    1191     .06       0    1240     .12       0
Bank Sta=1191,1240
XS Rating Curve= 0
Exp/Cntr=.3,.1

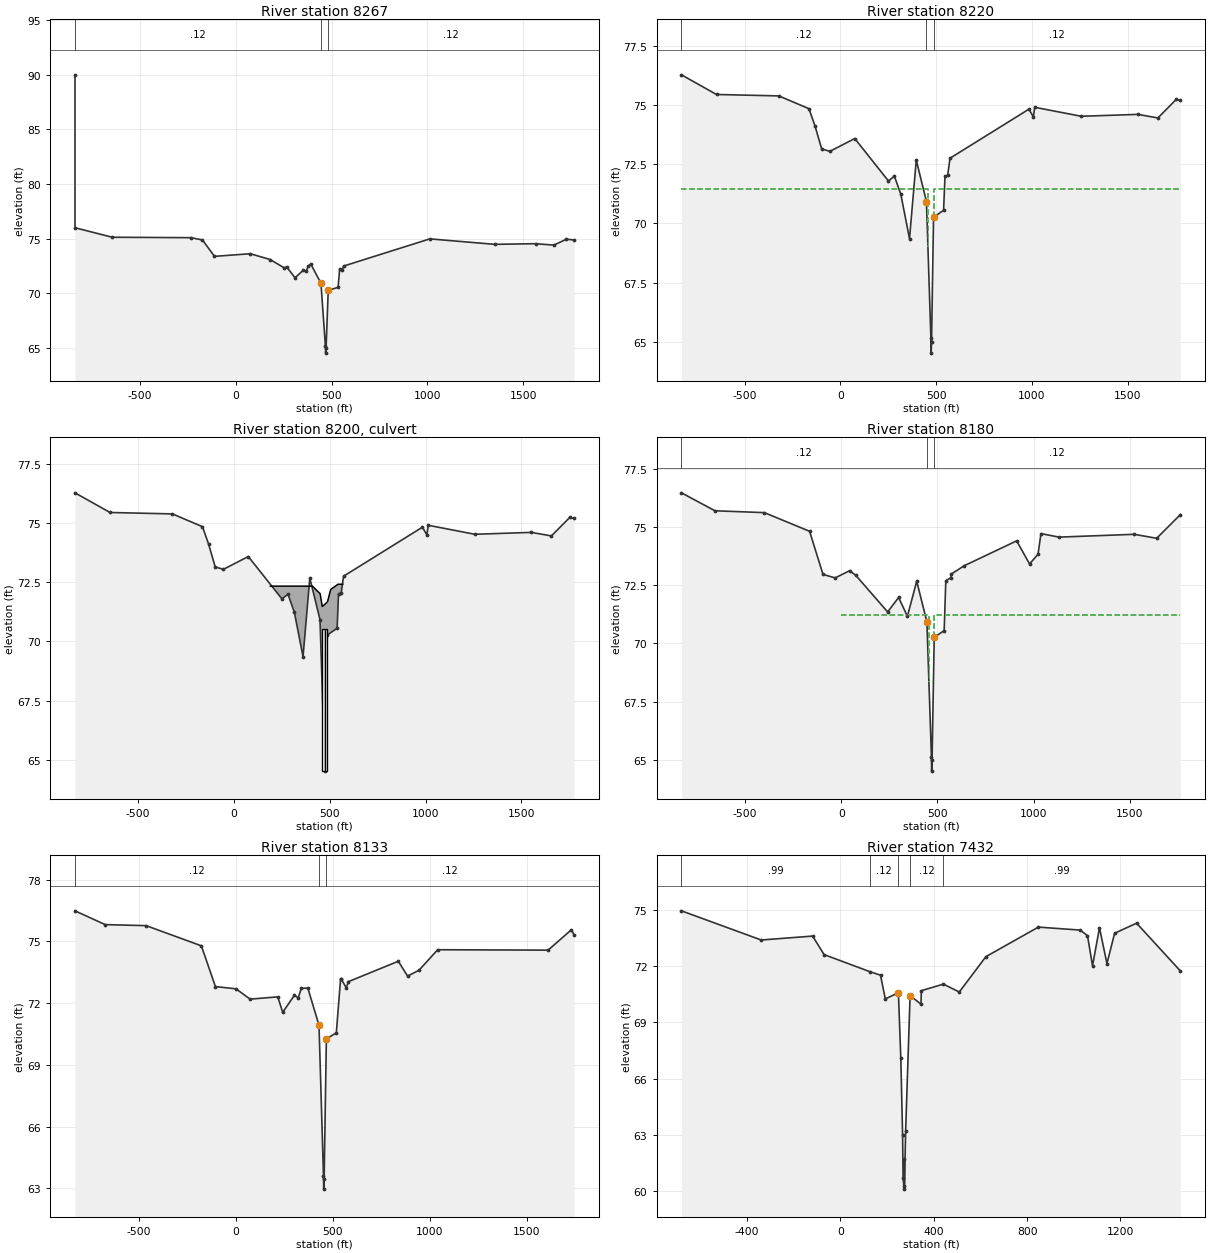
Type RM Length L Ch R = 1 ,8267    ,52,47,51
BEGIN DESCRIPTION:
copy of 483s5d, xs 4/4 Unnamed Field Rd
Bank Station Offset = -840
Raised Elev. between CB's by 1.56 ft based on known elevation for downstream invert of box culverts(483s5c) and x-sec survey data at RS 8133(483s5d). Adjusted contraction coefficient to 0.3 and expansion coefficient to 0.5
END DESCRIPTION:
XS GIS Cut Line= 6
     3209366.85813955532.6999999     3209366.858      13956372.7
     3209361.868    13956736.892      3209364.27    13956795.289
     3209378.148    13956883.995 3209345.104598713958135.8960277
#Sta/Elev= 30
    -840      90    -840      76 -645.52   75.13 -235.68   75.09 -174.46   74.88
 -111.84   73.38   75.66   73.62  178.56   73.09  252.07   72.33  265.32   72.41
   308.5   71.42  350.45   72.09  366.83   72.01  378.27    72.5  390.99   72.67
     444   70.92  467.39   65.14  468.67   64.52  470.76      65     482   70.26
  533.57   70.55  541.92   72.25  556.18   72.16  561.86   72.49 1012.22   74.98
 1351.46   74.48 1564.21   74.54 1659.74   74.41 1725.37   74.95 1764.97   74.88
#Mann= 3 , 0 , 0
    -840     .12       0     444     .06       0     482     .12       0
Bank Sta=444,482
XS Rating Curve= 0
Exp/Cntr=.5,.3

Type RM Length L Ch R = 1 ,8220    ,43,40,44
BEGIN DESCRIPTION:
copy of 483s5d, xs 3/4 Unnamed Field Rd
Bank Station Offset = -830
Raised Elev. between CB's by 1.56 ft based on known elevation for downstream invert of box culverts(483s5c) and x-sec survey data at RS 8133(483s5d). Adjusted contraction coefficient to 0.3 and expansion coefficient to 0.5. Manning's n for main channel changed from .06 to .04(min. for improved earthen channel) based on photos 483s4p1 &p8. Inserted block from x-sec station 0 to 2582.77 at elev. of 76 ft.
END DESCRIPTION:
XS GIS Cut Line= 6
 3209341.508236213955530.0397716     3209310.802    13956731.869
     3209317.144    13956788.894     3209325.729    13956825.807
     3209331.022      13956877.6 3209306.112582113958132.8760853
#Sta/Elev= 30
    -830   76.27 -646.99   75.44 -321.49   75.38 -164.46   74.84 -132.76   74.11
   -97.9   73.14  -55.09   73.04   74.74   73.58  250.46   71.79  281.83   71.99
  315.43   71.22  360.51   69.35  395.83   72.67     449   70.92  472.23   65.14
  473.51   64.52   475.6      65     486   70.26  538.41   70.55  545.83      72
  559.57   72.02  572.16   72.75  983.91   74.82 1007.18   74.49 1014.19    74.9
  1257.3   74.52 1552.47    74.6 1657.13   74.45 1752.77   75.23 1775.08   75.19
#Mann= 3 ,-1 , 0
    -830     .12       0     449     .04       0     486     .12       0
#XS Ineff= 2 , 0
    -830  457.26   71.47  489.76    -830   71.47
Permanent Ineff=
       F       F
#Block Obstruct= 2 , 0
    -830    -830      76 1752.77    -830      76
Bank Sta=449,486
XS Rating Curve= 0
Exp/Cntr=.5,.3

Type RM Length L Ch R = 2 ,8200    ,,,
BEGIN DESCRIPTION:
483s5: Unnamed Road (2-12'x6' Concrete Box Culverts)
Notes: Aligned box culverts in channel based on survey notes from 483s5c and low point shown in plot at Upstream and Downstream x-sec.  Set ineffective flow at bounding river stations @ elev. 71.47'. Extended deck on left to x-sec station 1020--US & x-section sta 970--DS @ elev. 72.33' and on right to station 1397.34@ elev. 72.41'.
END DESCRIPTION:
Bridge Culvert--1,0,-1,-1, 0
Deck Dist Width WeirC Skew NumUp NumDn MinLoCord MaxHiCord MaxSubmerge Is_Ogee
10,20,2.6,0, 10, 10, 71.47, , .95, 0, 0,0,,
     190  409.64  449.87  460.76  474.31  475.14  488.57  504.84  542.78  567.34
   72.33   72.33   72.01   71.47   71.56   71.57   71.68   72.19   72.41   72.41
       0       0       0       0       0       0       0       0       0       0
     140  409.64  449.87  460.76  474.31  475.14  488.57  504.84  542.78  567.34
   72.33   72.33   72.01   71.47   71.56   71.57   71.68   72.19   72.41   72.41
       0       0       0       0       0       0       0       0       0       0
BR Coef=-1 , 0 , 0 ,, 0 ,,,.8,0,,0,
WSPro=,,,, 1 ,,,, 0 ,,,, 0 ,,,,-1 ,-1 ,-1 , 0 , 0 , 0 , 0 , 0
Multiple Barrel Culv=2,6,12,30,.012,.5,1,10,1,64.54,64.52, 2,Field Rd    , 0 ,5
     467     463     480     476
Culvert Bottom n=.012
BC Design=,, 0 ,, 0 ,,,,,,

Type RM Length L Ch R = 1 ,8180    ,54,46,127
BEGIN DESCRIPTION:
copy of 483s5d, xs 2/4 Unnamed Field Rd
Bank Station Offset = -830
Raised Elev. between CB's by 1.56 ft based on known elevation for downstream invert of box culverts(483s5c) and x-sec survey data at RS 8133(483s5d). Adjusted contraction coefficient to 0.3 and expansion coefficient to 0.5. Manning's n for main channel changed from .06 to .04(min. for improved earthen channel) based on photos 483s4p1 &p8.
END DESCRIPTION:
XS GIS Cut Line= 6
 3209300.842876913955522.3002592     3209268.945    13956730.194
     3209277.866    13956785.917      3209286.45    13956822.831
     3209291.744    13956874.624 3209248.9387314 13958111.292584
#Sta/Elev= 30
    -830   76.46 -655.99   75.69 -399.15   75.61 -164.44   74.81  -94.72   72.96
  -31.51   72.81    43.6   73.12   75.57   72.92  241.02   71.35  298.08   71.97
  343.75   71.16  392.06   72.67     445   70.92  468.46   65.14  469.74   64.52
  471.83      65     483   70.26  534.64   70.55  543.25   72.69  569.91   72.82
  572.56   72.98  638.38   73.33  911.27    74.4  978.14   73.41 1022.05   73.82
 1037.53   74.71 1131.26   74.56 1521.88   74.68 1638.55   74.51 1762.12   75.53
#Mann= 3 ,-1 , 0
    -830     .12       0     445     .04       0     483     .12       0
#XS Ineff= 2 , 0
       0  455.49   71.23  483.99       0   71.23
Permanent Ineff=
       F       F
Bank Sta=445,483
XS Rating Curve= 0
Exp/Cntr=.5,.3

Type RM Length L Ch R = 1 ,8133    ,644,701,975
BEGIN DESCRIPTION:
483s5d, xs 1/4 Unnamed Field Rd
Bank Station Offset = -830
END DESCRIPTION:
XS GIS Cut Line= 6
 3209260.381216913955522.4833634     3209219.769    13956725.737
     3209232.688    13956775.373     3209257.166    13956882.804
     3209249.361     13957103.94 3209224.151738913958091.5470639
#Sta/Elev= 30
    -830   76.48 -674.23   75.81 -462.89   75.76 -177.99   74.78 -105.58    72.8
    1.17   72.69   73.22   72.19  216.21    72.3  241.65   71.55   302.4   72.38
  322.05   72.25  337.32   72.71  371.21   72.73     429   70.92  452.13   63.58
  453.41   62.96   455.5   63.44     467   70.26  518.31   70.55  540.36   73.17
   542.7   73.18  569.65   72.74  580.82   73.04  838.09   74.03  886.09   73.31
  944.54   73.59 1041.32   74.59  1611.1   74.57 1731.14   75.56 1744.62   75.32
#Mann= 3 , 0 , 0
    -830     .12       0     429     .06       0     467     .12       0
Bank Sta=429,467
XS Rating Curve= 0
Exp/Cntr=.3,.1

Type RM Length L Ch R = 1 ,7432    ,51,46,47
BEGIN DESCRIPTION:
483s4u, xs 4/4 Fairway Oaks Dr
Bank Station Offset = -680
Adjusted contraction coefficient to 0.3 and expansion coefficient to 0.5. Raised CB stations based on CB elevations @ RS 8133 (483s5d).
END DESCRIPTION:
XS GIS Cut Line= 6
 3208599.559792213955633.6092107     3208621.924    13956438.695
     3208611.478    13956574.488     3208603.944    13956594.485
     3208601.032    13956712.893 3208548.217340713957766.8660276
#Sta/Elev= 30
    -680   74.97 -338.61   73.41 -118.28   73.62  -69.28   72.63  126.16   71.72
  172.33   71.53  192.86   70.26     249   70.59  259.29   67.09     267   62.96
  269.08   60.67  272.59   60.25  273.82   61.69  274.65   60.09     280   63.22
     299   70.44  345.61   69.98  347.22    70.7  441.52   71.05   509.7   70.63
  623.58   72.52  848.48    74.1 1027.33   73.94 1058.69   73.64 1080.23   72.03
 1110.01   74.06 1142.01   72.15 1174.78   73.77 1268.83   74.31 1456.79   71.75
#Mann= 5 ,-1 , 0
    -680     .99       0  126.16     .12       0     249     .06       0
     299     .12       0  441.52     .99       0
#Block Obstruct= 2 , 0
       0                 1268.83       0   74.31
Bank Sta=249,299
XS Rating Curve= 0
Exp/Cntr=.5,.3

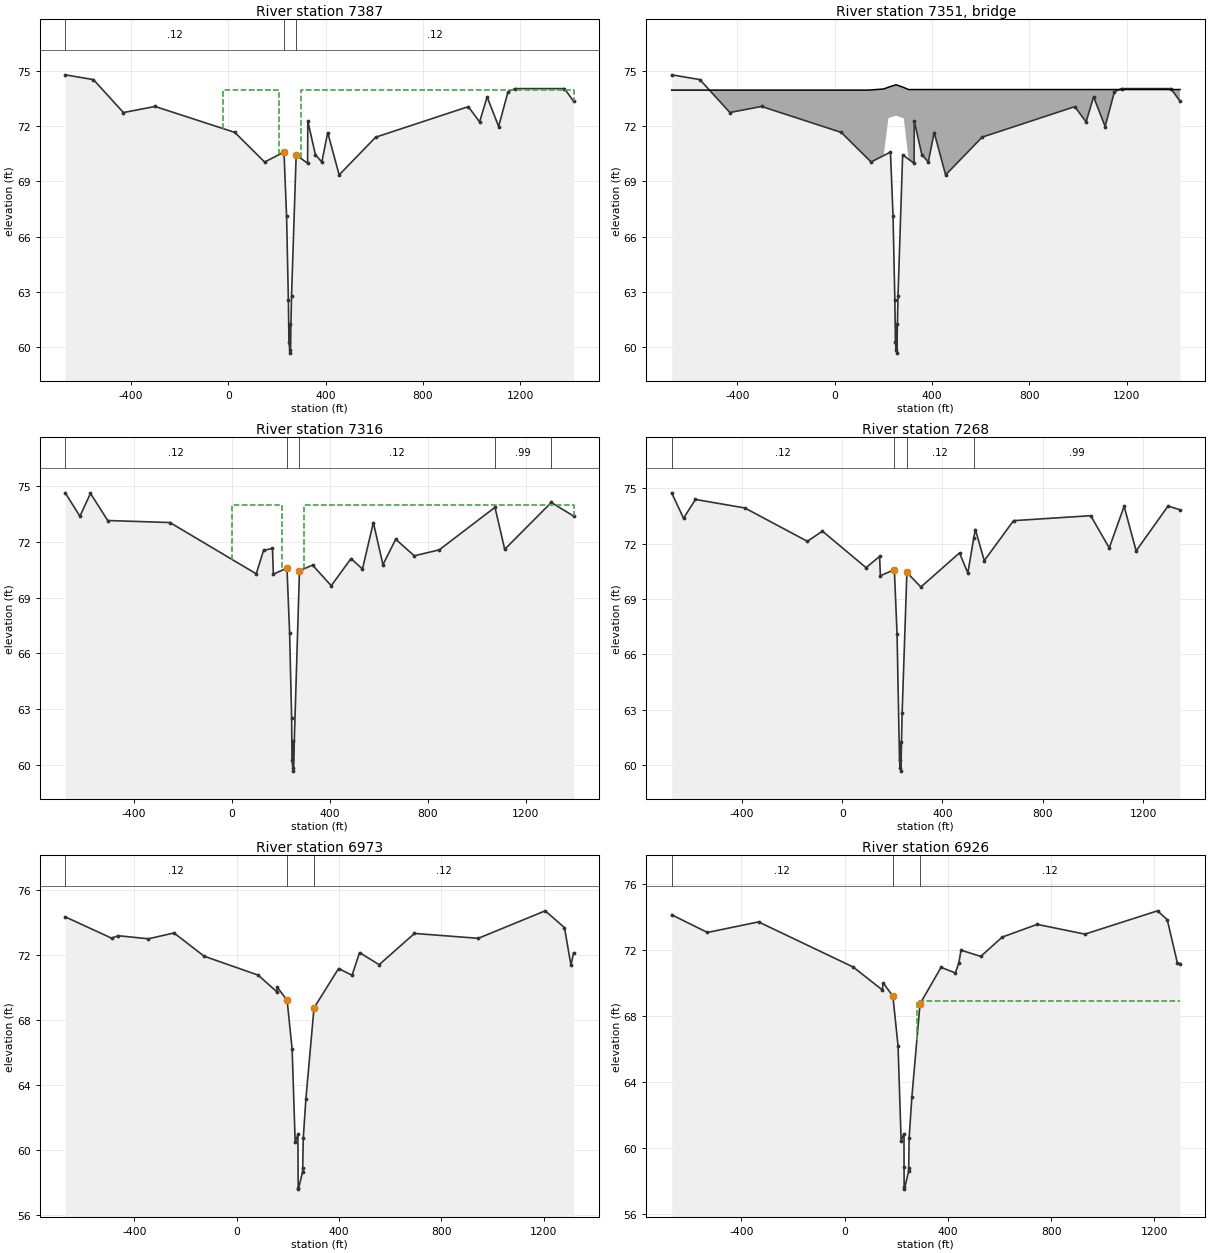
Type RM Length L Ch R = 1 ,7387    ,68,71,73
BEGIN DESCRIPTION:
copy of 483s4u, xs 3/4 Fairway Oaks Dr
Bank Station Offset = -670
Lowered Elev. at and between CB's by 0.43 ft based on known elevation for downstream invert at (483s4c) and x-sec survey data at RS 7432(483s4u). Adjusted contraction coefficient to 0.3 and expansion coefficient to 0.5. Used x-sec sta 924.96 for sta equation. Raised CB stations based on CB elevations @ RS 8133 (483s5d).
END DESCRIPTION:
XS GIS Cut Line= 6
     3208571.566    13955639.804     3208571.924    13956438.695
     3208570.183     13956484.83     3208561.478    13956574.488
     3208543.373    13956814.915  3208513.54109513957726.7929081
#Sta/Elev= 30
    -670   74.79 -554.09   74.53 -430.82   72.74  -300.7   73.07   26.72   71.66
  149.38   70.05     229   70.59   239.6   67.09     247   62.53  249.39   60.24
   252.9   59.82  254.13   61.26  254.96   59.66     260   62.79     279   70.44
  325.92   69.98  326.78   72.28  357.91   70.45  384.34   70.05  408.62   71.65
  455.59   69.35  605.71    71.4  986.27   73.06 1032.73   72.23  1063.6   73.59
 1110.96   71.98 1149.37   73.87 1178.59   74.04 1381.04   74.04 1418.63   73.36
#Mann= 3 , 0 , 0
    -670     .12       0     229     .06       0     279     .12       0
#XS Ineff= 2 , 0
  -19.79  207.35   73.96  297.27  -19.79   73.96
Permanent Ineff=
       F       F
Bank Sta=229,279
XS Rating Curve= 0
Exp/Cntr=.5,.3

Type RM Length L Ch R = 3 ,7351    ,,,
BEGIN DESCRIPTION:
483s4: Fairway Oaks Dr.
Notes: (length 63')  Extended deck on left to x-sec station 0 @ elev. 73.96' and on right to station 2088.63@ elev. 73.99' for upstream and 2074.47@elev. 73.99'. Set ineffective flow at bounding river stations @ elev. 73.96'. CB sta @ bounding x-sections were raised based on elevations of CB's at RS 8133(483s5d)
END DESCRIPTION:
Bridge Culvert--1,0,-1,-1, 0
Deck Dist Width WeirC Skew NumUp NumDn MinLoCord MaxHiCord MaxSubmerge Is_Ogee
18,35,2.6,0, 9, 9, 73.96, , .95, 0, 0,0,,
    -670  138.74  201.15  220.79  252.08  283.81  303.37  386.94 1418.63
   73.96   73.96   74.02   74.12   74.25    74.1   73.99   73.99   73.99
       0       0       0   72.44   72.57   72.42       0       0       0
    -680  134.97  197.38  217.02  248.31  280.04   299.6  383.17 1394.47
   73.96   73.96   74.02   74.12   74.25    74.1   73.99   73.99   73.99
       0       0       0   72.44   72.57   72.42       0       0       0
BR Coef=-1 , 0 , 0 ,, 0 ,,,.8,-1,,0,
WSPro=,,,, 1 ,,,, 0 ,,,, 0 ,,,,-1 ,-1 ,-1 , 0 , 0 , 0 , 0 , 0
BC Design=,, 0 ,, 0 ,,,,,,

Type RM Length L Ch R = 1 ,7316    ,41,48,45
BEGIN DESCRIPTION:
copy of 483s4u, xs 2/4 Fairway Oaks Dr
Bank Station Offset = -680
Lowered Elev. at and between CB's by 0.43 ft based on known elevation for downstream invert at (483s4c) and x-sec survey data at RS 7432(483s4u). Adjusted contraction coefficient to 0.3 and expansion coefficient to 0.5. Used x-sec sta 931.19 for sta equation. Raised CB stations based on CB elevations @ RS 8133 (483s5d). Used 0.99 for Manning's "n" as indicated below
END DESCRIPTION:
XS GIS Cut Line= 6
 3208493.249829213955661.3368905     3208501.647    13956427.007
     3208496.475    13956522.691     3208488.717    13956714.059
     3208478.373    13956814.915 3208442.283389213957734.2143685
#Sta/Elev= 30
    -680   74.64 -620.06   73.38  -576.8   74.61 -506.55   73.15 -252.48   73.04
   99.64   70.28  129.39   71.54  165.89   71.65   169.4   70.26     225   70.59
  235.83   67.09     244   62.53  245.62   60.24  249.13   59.82  250.36   61.26
  251.19   59.66     276   70.44   329.6   70.75  405.64   69.64  486.41    71.1
  533.07   70.54  577.55   73.04  616.79   70.77  668.69   72.14  744.64   71.25
  846.36   71.57 1073.93   73.86 1113.63    71.6 1303.64   74.12 1394.47   73.39
#Mann= 5 ,-1 , 0
    -680     .12       0     225     .06       0     276     .12       0
 1073.93     .99       0 1303.64     .12       0
#XS Ineff= 2 , 0
    2.53  203.58   73.96   293.5    2.53   73.96
Permanent Ineff=
       F       F
Bank Sta=225,276
XS Rating Curve= 0
Exp/Cntr=.5,.3

Type RM Length L Ch R = 1 ,7268    ,293,295,296
BEGIN DESCRIPTION:
copy of 483s4u, xs 1/4 Fairway Oaks Dr
Bank Station Offset = -680
Lowered Elev. at and between CB's by 0.43 ft based on known elevation for downstream invert at (483s4c) and x-sec survey data at RS 7432(483s4u).  Raised CB stations based on CB elevations @ RS 8133 (483s5d). Used 0.99 for Manning's "n" as indicated below
END DESCRIPTION:
XS GIS Cut Line= 6
 3208424.5648387 13955702.488702     3208460.647    13956427.007
     3208455.475    13956522.691     3208447.717    13956714.059
     3208437.373    13956814.915     3208437.37313957727.9230428
#Sta/Elev= 30
    -680   74.76 -632.73   73.38  -585.1    74.4 -388.52   73.94 -138.85   72.13
  -78.65   72.68   95.25    70.7  149.12   71.31  152.41   70.26     208   70.59
  218.84   67.09  228.63   60.24  232.14   59.82  233.37   61.26   234.2   59.66
     239   62.79     258   70.44  313.73   69.65   467.9    71.5  501.09   70.41
  524.65   72.31  531.12   72.77  566.61   71.08  683.49   73.25  991.09   73.52
 1065.01   71.77 1124.34   74.03 1172.21   71.61 1299.38   74.04 1347.17   73.84
#Mann= 4 ,-1 , 0
    -680     .12       0     208     .06       0     258     .12       0
  524.65     .99       0
Bank Sta=208,258
XS Rating Curve= 0
Exp/Cntr=.3,.1

Type RM Length L Ch R = 1 ,6973    ,44,47,48
BEGIN DESCRIPTION:
483s3u, xs 4/4 Lk Houston GC Hole #6
Bank Station Offset = -670
Adjusted contraction coefficient to 0.3 and expansion coefficient to 0.5. Raised CB stations based on elevations taken @ pier inverts. Inserted block from x-sec sta 0 to 1875.34 @ elev of 74.69.
END DESCRIPTION:
XS GIS Cut Line= 6
 3208203.631859513955786.4196014      3208161.58    13956562.025
     3208162.289    13956715.791     3208160.872     13956766.81
     3208155.272    13956825.297 3208204.981093113957769.5230728
#Sta/Elev= 30
    -670   74.32 -488.95   73.01 -463.19   73.16 -344.78   72.97  -244.9   73.33
 -127.22    71.9    83.4   70.74  157.03   69.71  158.27      70     197   69.19
   216.6   66.17  228.46   60.45     239   60.94  240.27   57.68  241.21   57.58
  257.32   58.65  257.82   58.85     260    60.7  270.21    63.1     302   68.72
  397.93   71.14  450.79   70.73  479.78   72.12  556.61   71.38  694.47    73.3
  943.79      73 1205.35   74.69 1280.51   73.66 1305.89   71.35 1315.91   72.11
#Mann= 3 ,-1 , 0
    -670     .12       0     197     .06       0     302     .12       0
#Block Obstruct= 2 , 0
    -670    -670   74.69 1205.34    -670   74.69
Bank Sta=197,302
XS Rating Curve= 0
Exp/Cntr=.5,.3

Type RM Length L Ch R = 1 ,6926    ,20,20,20
BEGIN DESCRIPTION:
copy of 483s3u, xs 3/4 Lk Houston GC Hole #6
Bank Station Offset = -670
Lowered Elev. between CB's by 0.07 ft based on known elevation for downstream invert at (483s3c) and x-sec survey data at RS 6973(483s3u). Adjusted contraction coefficient to 0.3 and expansion coefficient to 0.5. Raised CB stations based on elevations taken @ pier inverts. Inserted block from x-sec sta 0 to 1858.69 @ elev of 74.43.
END DESCRIPTION:
XS GIS Cut Line= 6
 3208183.479693913955785.0707818     3208122.222    13956566.203
     3208115.093    13956661.116     3208106.181     13956768.06
 3208031.781050513957716.2982658 3208029.276427313957748.2200561
#Sta/Elev= 30
    -670   74.11 -531.44   73.04 -333.51   73.68   33.11   70.95  146.19   69.56
  148.64      70     187   69.19  206.97   66.17  218.83   60.45     230   60.87
  230.17   58.83  230.64   57.61  231.58   57.51  247.69   58.58  248.19   58.78
     250   60.63  260.58    63.1     292   68.72  373.68   70.93  428.86   70.59
  442.45   71.19  450.91   71.97  527.47   71.59  610.43   72.76  745.97   73.53
  930.94   72.94 1212.22   74.35 1249.94   73.81 1289.11   71.19  1299.2   71.16
#Mann= 3 ,-1 , 0
    -670     .12       0     187     .06       0     292     .12       0
#XS Ineff= 2 , 0
    -670  174.97   68.87  279.81    -670   68.87
Permanent Ineff=
       F       F
#Block Obstruct= 2 , 0
    -670    -670   74.43 1188.69    -670   74.43
Bank Sta=187,292
XS Rating Curve= 0
Exp/Cntr=.5,.3

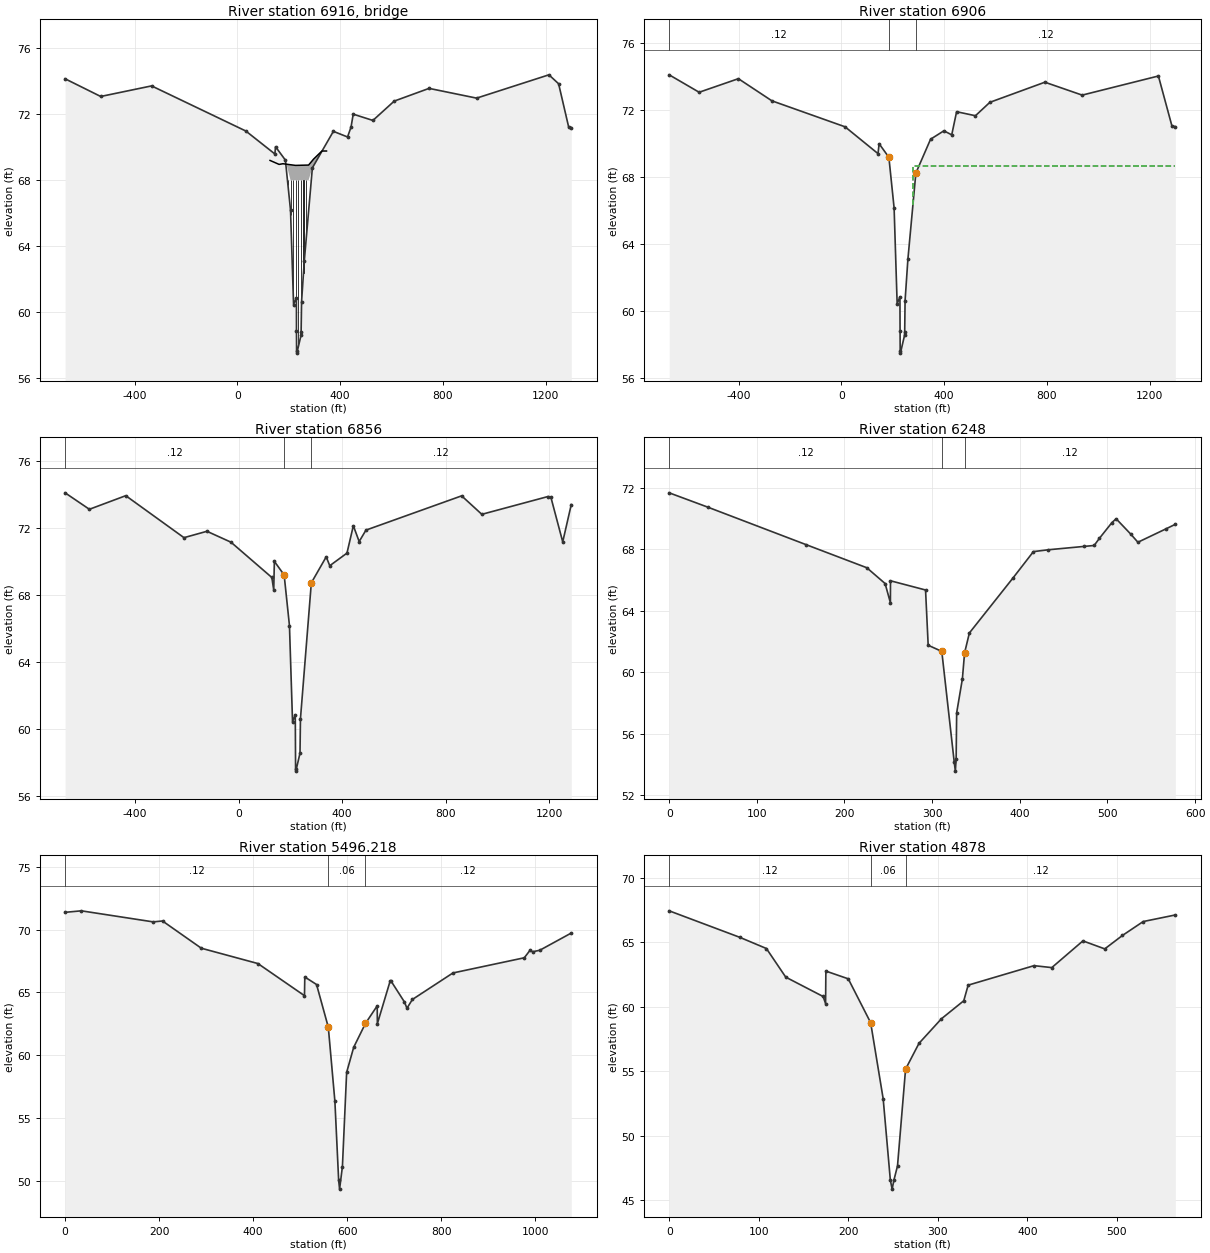
Type RM Length L Ch R = 3 ,6916    ,,,
BEGIN DESCRIPTION:
483s3: Golf Cart Path  (Hole #6)  Notes: Length 100' w/9 pier sets, Pier #4 center line stationing was adjusted to 10' O.C. between Piers #3 and #5. Set ineffective flow at bounding river stations @ elev. 68.87'. Used internal bridge x-sec based on survey pts and elevations @ pier inverts. Internal DS pt 854.95 lowered from elev. 68' to 67.90' to show bridge opening.Extended deck on right to x-sec station 1017.02 @ elev. 69.74'
END DESCRIPTION:
Bridge Culvert--1,0,-1,-1, 0
Deck Dist Width WeirC Skew NumUp NumDn MinLoCord MaxHiCord MaxSubmerge Is_Ogee
5,10,2.6,0, 8, 8, 68.87, , .95, 0, 0,0,,
  127.27  162.51  177.47  226.33  277.31  296.68  329.15  347.02
   69.17   68.93   68.97   68.87   68.89   69.25   69.74   69.74
       0       0   67.98   67.98   67.98       0       0       0
  127.27  162.51  177.47  226.33  277.31  296.68  329.15  347.02
   69.17   68.93   68.97   68.87   68.89   69.25   69.74   69.74
       0       0   67.98   67.98   67.98       0       0       0
Pier Skew, UpSta & Num, DnSta & Num=  ,187.7, 2 ,187.7, 2 , 0 , 0 , 0 ,,
      .8      .8
    57.5   68.04
      .8      .8
    57.5   68.04
Pier Skew, UpSta & Num, DnSta & Num=  ,196.94, 2 ,196.94, 2 , 0 , 0 , 0 ,0,
      .8      .8
    57.5   68.04
      .8      .8
    57.5   68.04
Pier Skew, UpSta & Num, DnSta & Num=  ,207.57, 2 ,207.57, 2 , 0 , 0 , 0 ,0,
      .8      .8
    57.5   68.04
      .8      .8
    57.5   68.04
Pier Skew, UpSta & Num, DnSta & Num=  ,217.32, 2 ,217.32, 2 , 0 , 0 , 0 ,0,
      .8      .8
    57.5   68.04
      .8      .8
    57.5   68.04
Pier Skew, UpSta & Num, DnSta & Num=  ,227.6, 2 ,227.6, 2 , 0 , 0 , 0 ,0,
      .8      .8
    57.5   68.04
      .8      .8
    57.5   68.04
Pier Skew, UpSta & Num, DnSta & Num=  ,236.89, 2 ,236.89, 2 , 0 , 0 , 0 ,0,
       1       1
    57.5   68.04
       1       1
    57.5   68.04
Pier Skew, UpSta & Num, DnSta & Num=  ,247.58, 2 ,247.58, 2 , 0 , 0 , 0 ,0,
      .8      .8
    57.5   68.04
      .8      .8
    57.5   68.04
Pier Skew, UpSta & Num, DnSta & Num=  ,257.52, 2 ,257.52, 2 , 0 , 0 , 0 ,0,
      .8      .8
    57.5   68.04
      .8      .8
    57.5   68.04
Pier Skew, UpSta & Num, DnSta & Num=  ,267.83, 2 ,267.83, 2 , 0 , 0 , 0 ,0,
      .8      .8
    57.5   68.04
      .8      .8
    57.5   68.04
BR Coef=-1 , 0 , 0 ,, 0 ,,,.8,-1,,0,
WSPro=,,,, 1 ,,,, 0 ,,,, 0 ,,,,-1 ,-1 ,-1 , 0 , 0 , 0 , 0 , 0
BC Design=,, 0 ,, 0 ,,,,,,

Type RM Length L Ch R = 1 ,6906    ,50,50,50
BEGIN DESCRIPTION:
copy of 483s3u, xs 2/4 Lk Houston GC Hole #6
Bank Station Offset = -670
Lowered Elev. at and between CB's by 0.07 ft based on known elevation for downstream invert at (483s3c) and x-sec survey data at RS 6973(483s3u). Adjusted contraction coefficient to 0.3 and expansion coefficient to 0.5. Raised CB stations based on elevations taken @ pier inverts. Inserted block from x-sec sta 0 to 1862.74 @ elev of 74.19.
END DESCRIPTION:
XS GIS Cut Line= 6
 3208136.641599913955790.9313366     3208102.222    13956566.203
     3208095.093    13956661.116     3208086.181     13956768.06
 3207962.476002913957709.3921967 3207957.010137113957750.9846594
#Sta/Elev= 30
    -670   74.11  -553.4   73.07 -400.68   73.88  -270.4   72.56   14.37   71.01
  142.68   69.41     147      70     185   69.19  205.33   66.17  217.19   60.45
     228   60.87  228.53   58.83     229   57.61  229.94   57.51  246.05   58.58
  246.55   58.78     248   60.63  258.94    63.1     290   68.25  347.28   70.27
  399.05   70.77  429.58   70.53  448.55   71.91  521.86   71.67  578.05   72.47
  792.11   73.67  937.22    72.9 1233.92   74.04  1286.4   71.07 1299.91   71.02
#Mann= 3 ,-1 , 0
    -670     .12       0     185     .06       0     290     .12       0
#XS Ineff= 2 , 0
       0  174.97   68.65   278.4       0   68.65
Permanent Ineff=
       F       F
#Block Obstruct= 2 , 0
    -670    -670   74.19 1192.74    -670   74.19
Bank Sta=185,290
XS Rating Curve= 0
Exp/Cntr=.5,.3

Type RM Length L Ch R = 1 ,6856    ,589,608,624
BEGIN DESCRIPTION:
copy of 483s3u, xs 1/4 Lk Houston GC Hole #6
Bank Station Offset = -670
Lowered Elev. at and between CB's by 0.07 ft based on known elevation for downstream invert at (483s3c) and x-sec survey data at RS 6973(483s3u).Raised CB stations based on elevations taken @ pier inverts.  Inserted block from x-sec sta 0 to 1865.14 @ elev of 73.86.
END DESCRIPTION:
XS GIS Cut Line= 6
     3208064.74413955792.3269999     3208064.744    13956462.327
     3208052.222    13956566.203     3208045.093    13956661.116
     3208036.181     13956768.06 3207942.8976676 13957741.412101
#Sta/Elev= 30
    -670   74.08 -576.21    73.1 -435.69   73.91 -210.86   71.41 -122.14   71.79
  -29.24   71.14  128.45   69.04  135.85   68.29  138.22      70     176   69.19
  196.55   66.17  208.41   60.45     219   60.87  220.22   57.61  221.16   57.51
  237.27   58.58     239   60.63     281   68.72   338.5   70.27  352.15   69.74
  418.62   70.49  443.24   72.12  465.76   71.18  492.03   71.86  861.51    73.9
   939.5    72.8 1195.14   73.86 1206.35   73.81 1251.95   71.16 1284.94   73.38
#Mann= 3 ,-1 , 0
    -670     .12       0     176     .06       0     281     .12       0
#Block Obstruct= 2 , 0
    -670    -670   73.86 1195.14    -670   73.86
Bank Sta=176,281
XS Rating Curve= 0
Exp/Cntr=.3,.1

Type RM Length L Ch R = 1 ,6248    ,793.63,751.64,718.97
BEGIN DESCRIPTION:
483v2 Notes: Inserted block at sta 0 to 509.92 @ elev. 69.99.
END DESCRIPTION:
XS GIS Cut Line= 6
      3207533.07    13956186.417     3207493.801    13956435.723
     3207475.465    13956475.002     3207455.868    13956517.057
     3207434.799    13956562.475     3207407.546    13956745.744
#Sta/Elev= 29
       0   71.68   44.36   70.74  155.92   68.31  225.45    66.8  246.34   65.77
  252.38   64.52  252.48   65.95  292.48   65.35  295.48   61.75     311   61.35
  325.18   54.15  326.48   53.55  327.38   54.35  327.98   57.35  334.48   59.55
     337   61.25  342.48   62.55  392.48   66.15  415.53   67.85  432.47   67.97
  473.53   68.19  484.85   68.25  490.76   68.71  505.11   69.74  509.92   69.99
  526.43      69  534.76   68.46  567.03   69.34  577.48   69.63
#Mann= 3 , 0 , 0
       0     .12       0     311     .06       0     337     .12       0
#Block Obstruct= 2 , 0
       0       0   69.99  509.92       0   69.99
Bank Sta=311,337
XS Rating Curve= 0
Exp/Cntr=.3,.1

Type RM Length L Ch R = 1 ,5496.218,544.12,618.1,653.61
BEGIN DESCRIPTION:
copy of 483v3
added 3.47ft to survey elevations for constant slope between XS 4878 and 6248
XS added 11/08/02
END DESCRIPTION:
XS GIS Cut Line= 4
      3206665.67    13956190.623     3206782.196    13956674.814
     3206889.467    13956767.361     3207045.115    13957175.411
#Sta/Elev= 30
       0   71.37   34.52   71.49  187.17   70.61  207.19   70.68  289.73   68.51
  410.03   67.29  509.07   64.73  509.74   66.22  534.74   65.62  559.74   62.22
  573.74   56.32  581.74   50.02  583.74   49.32  589.74   51.12  598.74   58.62
  613.74   60.62  638.74   62.52  663.74   63.92  664.07    62.5  691.03   65.87
  693.58   65.87  721.64   64.23  726.98   63.73   738.6   64.43  824.75   66.54
  976.53   67.75  988.58   68.34  994.56   68.23  1009.5   68.35 1076.42   69.72
#Mann= 3 , 0 , 0
       0     .12       0  559.74     .06       0  638.74     .12       0
#Block Obstruct= 2 , 0
       0     440      64               0
Bank Sta=559.74,638.74
XS Rating Curve= 0
Exp/Cntr=.3,.1

Type RM Length L Ch R = 1 ,4878    ,1083.07,1152.26,1065.68
BEGIN DESCRIPTION:
483v3
Notes:  Changed Manning's "n" value to 0.99 as indicated.
END DESCRIPTION:
XS GIS Cut Line= 4
     3206485.041     13956424.05     3206397.666    13956575.284
     3206288.577    13956684.117     3206168.077    13956887.668
#Sta/Elev= 26
       0   67.42    78.7   65.37  108.56    64.5  130.19   62.28  171.91   60.78
  174.66   60.23  174.99   62.75  199.99   62.15     225   58.75  238.99   52.85
  246.99   46.55  248.99   45.85  250.99   46.55  254.99   47.65     264   55.15
  278.99   57.15  303.99   59.05  328.99   60.45  333.89   61.66  407.46   63.17
  427.31   63.02  462.06   65.09  486.45   64.47  506.18   65.51  529.42   66.59
   565.3    67.1
#Mann= 3 ,-1 , 0
       0     .12       0     225     .06       0     264     .12       0
Bank Sta=225,264
XS Rating Curve= 0
Exp/Cntr=.3,.1