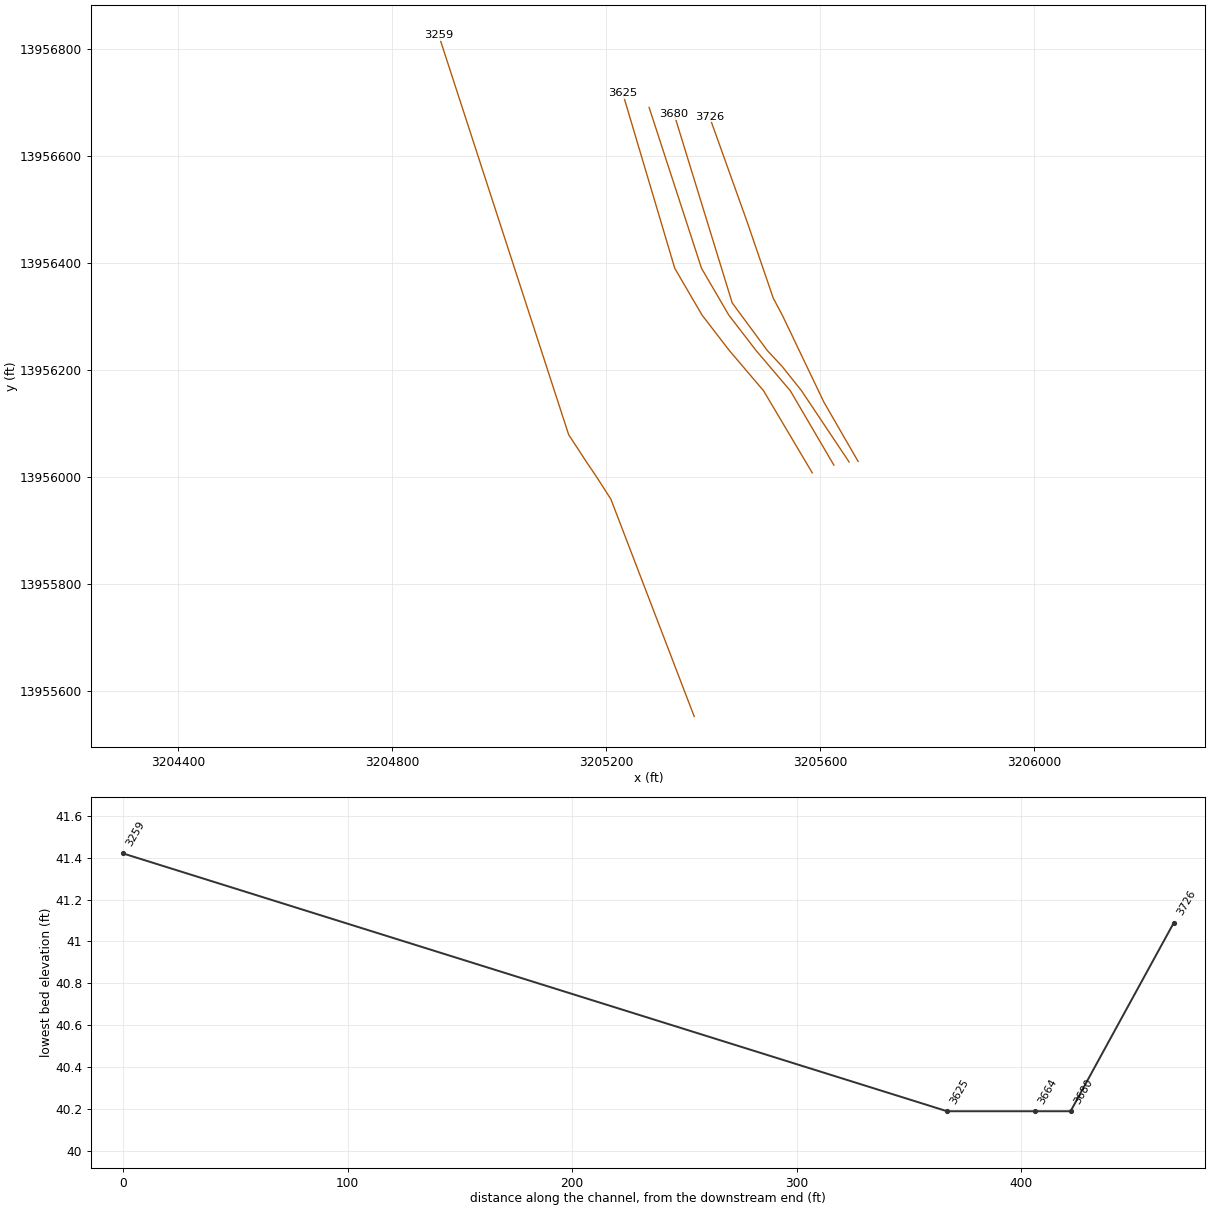
HEC-RAS study S110-00-00.prj: S110-00-00

--- S110-00-00.g02 (geometry) --- (continued)

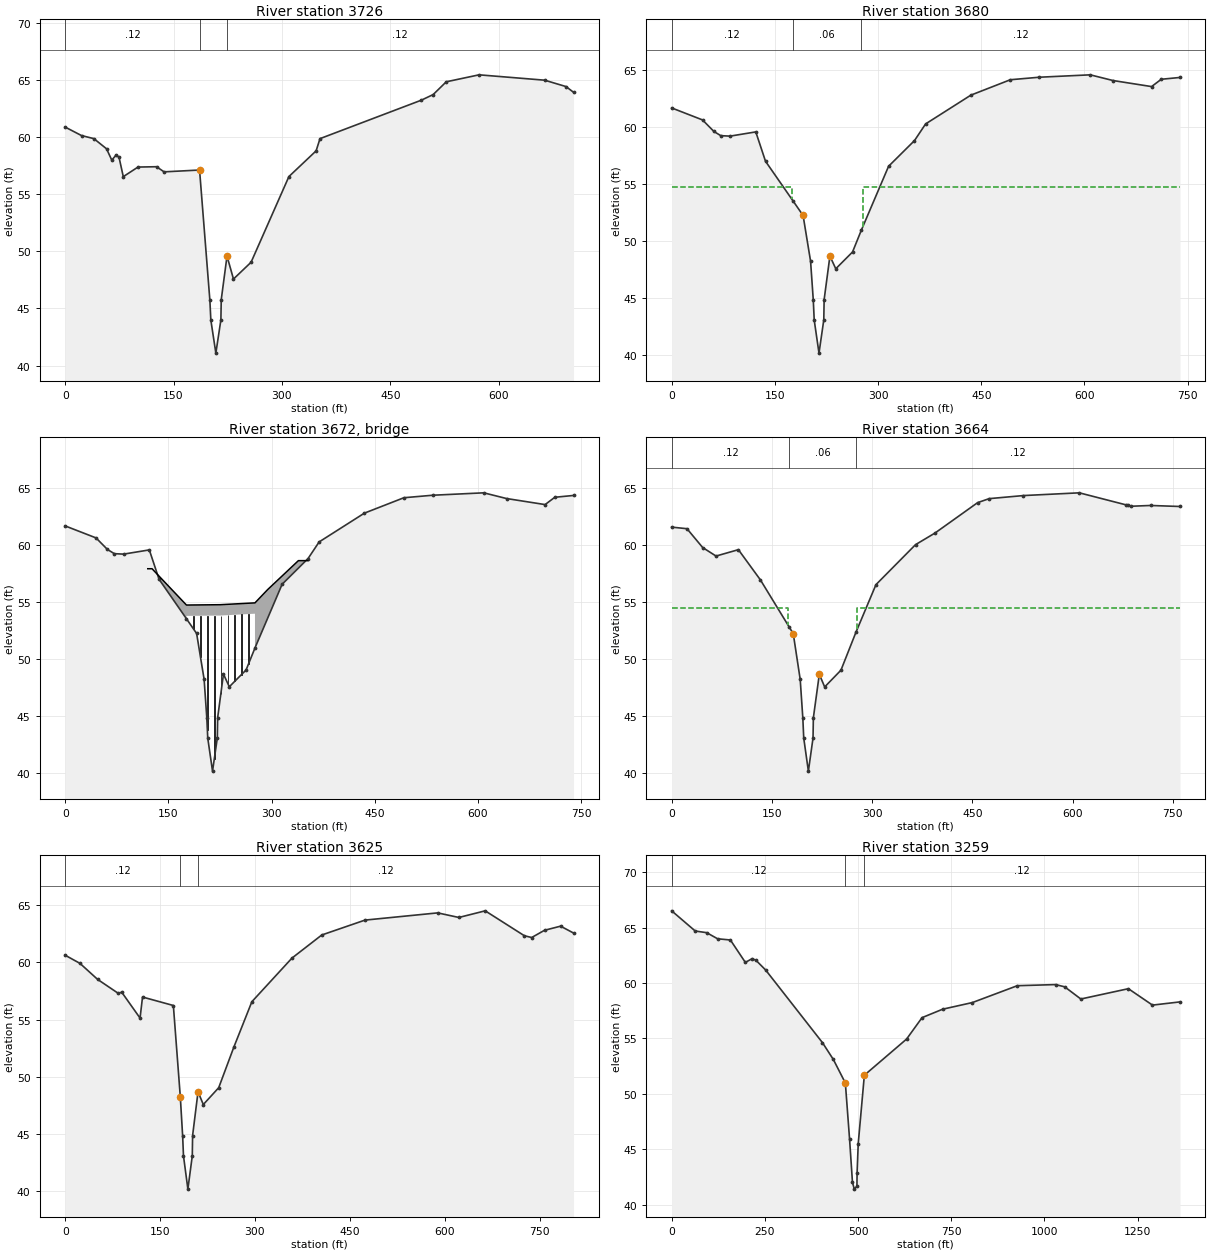
Type RM Length L Ch R = 1 ,3726    ,33,46,49
BEGIN DESCRIPTION:
483s2u, xs 4/4 Lk Houston GC Hole #9
Adjusted contraction coefficient to 0.3 and expansion coefficient to 0.5.
END DESCRIPTION:
XS GIS Cut Line= 6
     3205670.941     13956029.37     3205606.948    13956140.214
     3205529.694    13956301.838     3205512.414    13956334.366
     3205464.142    13956475.368     3205393.139    13956673.687
#Sta/Elev= 30
       0   60.89   22.58   60.15    39.7   59.88   57.22   58.99   64.47      58
   70.75   58.46   74.54   58.24   80.41   56.55  100.75   57.39   126.5   57.42
  136.84   56.97     186   57.13  200.27   45.72   201.6   43.99  208.55   41.09
  215.52      44  216.01   45.77     224   49.59  232.94   47.58   257.3   49.05
  309.71   56.56  347.36   58.81  352.73   59.88  493.07   63.25  509.36   63.74
  527.54   64.86  572.97   65.47  663.79      65  693.35   64.44  703.71   63.94
#Mann= 3 , 0 , 0
       0     .12       0     186     .06       0     224     .12       0
Bank Sta=186,224
XS Rating Curve= 0
Exp/Cntr=.5,.3

Type RM Length L Ch R = 1 ,3680    ,23,16,16
BEGIN DESCRIPTION:
copy of 483s2u, xs 3/4 Lk Houston GC Hole #9
Notes: Lowered elevations between main channel banks by 0.9 ft.  Also lowered left CB elevation from 57.13' to 52.25' to indicate piers/adbutment. Adjusted contraction coefficient to 0.3 and expansion coefficient to 0.5. Lowered elev. @ x-sec sta 133.16, 136.37, 141.27,& 142.41 to show deck. Adjusted Manning's n value to reflect bridge opening.
END DESCRIPTION:
XS GIS Cut Line= 6
     3205654.109    13956028.289      3205565.14     13956161.56
     3205528.546    13956207.303       3205501.1    13956236.782
     3205435.656    13956325.602     3205327.032    13956678.584
#Sta/Elev= 30
       0   61.67   44.84   60.62   61.35   59.61   71.39   59.24   84.89    59.2
  122.26   59.57  136.37      57  176.21   53.54     191   52.25  201.89   48.24
  205.84   44.82  207.17   43.09  214.12   40.19  221.09    43.1  221.58   44.87
     230   48.69  238.51   47.58  262.87   49.05  275.81   50.98  315.28   56.56
  352.93   58.81  369.09   60.27  434.85   62.79  492.24   64.14   534.4   64.36
  608.36   64.57  641.46   64.07   697.5   63.54  711.58   64.18  738.82   64.34
#Mann= 3 ,-1 , 0
       0     .12       0  176.21     .06       0  275.81     .12       0
#XS Ineff= 2 , 0
       0  174.21   54.74  277.81       0   54.74
Permanent Ineff=
       F       F
Bank Sta=191,230
XS Rating Curve= 0
Exp/Cntr=.5,.3

Type RM Length L Ch R = 3 ,3672    ,,,
BEGIN DESCRIPTION:
483s2: Golf Cart Path @Hole #9
Notes: (length 100' w/ 9 pier sets)  Used pier widths from survey notes. Extended deck on left to x-sec station 120 @ elev. 57.92' and on right to station 352.5 @ elev. 58.63'. Set ineffective flow at bounding river stations @ elev. 54.74'. Lowered left CB sta elev. at bounding stations from 57.13' to 52.25'.
END DESCRIPTION:
Bridge Culvert--1,0,-1,-1, 0
Deck Dist Width WeirC Skew NumUp NumDn MinLoCord MaxHiCord MaxSubmerge Is_Ogee
3,10,2.6,0, 8, 8, 54.74, , .95, 0, 0,0,,
     120  126.22  176.21  225.24  275.81  294.17  338.92   352.5
   57.92   57.92   54.74   54.77   54.93   56.09   58.63   58.63
                   53.79   53.82   53.98
     120  126.22  176.21  225.24  275.81  294.17  338.92   352.5
   57.92   57.92   54.74   54.77   54.93   56.09   58.63   58.63
                   53.79   53.82   53.98
Pier Skew, UpSta & Num, DnSta & Num=  ,186.51, 2 ,186.51, 2 , 0 , 0 , 0 ,,
      .8      .8
   41.08   53.98
      .8      .8
   41.08   53.98
Pier Skew, UpSta & Num, DnSta & Num=  ,196.56, 2 ,196.56, 2 , 0 , 0 , 0 ,,
      .8      .8
   41.08   53.98
      .8      .8
   41.08   53.98
Pier Skew, UpSta & Num, DnSta & Num=  ,206.61, 2 ,206.61, 2 , 0 , 0 , 0 ,,
      .8      .8
   41.08   53.98
      .8      .8
   41.08   53.98
Pier Skew, UpSta & Num, DnSta & Num=  ,216.7, 2 ,216.7, 2 , 0 , 0 , 0 ,,
       1       1
   41.08   53.98
       1       1
   41.08   53.98
Pier Skew, UpSta & Num, DnSta & Num=  ,226.2, 2 ,226.2, 2 , 0 , 0 , 0 ,,
      .8      .8
   41.08   53.98
      .8      .8
   41.08   53.98
Pier Skew, UpSta & Num, DnSta & Num=  ,236.6, 2 ,236.6, 2 , 0 , 0 , 0 ,,
      .8      .8
   41.08   53.98
      .8      .8
   41.08   53.98
Pier Skew, UpSta & Num, DnSta & Num=  ,246.36, 2 ,246.36, 2 , 0 , 0 , 0 ,,
      .8      .8
   41.08   53.98
      .8      .8
   41.08   53.98
Pier Skew, UpSta & Num, DnSta & Num=  ,256.25, 2 ,256.25, 2 , 0 , 0 , 0 ,,
       1       1
   41.08   53.98
       1       1
   41.08   53.98
Pier Skew, UpSta & Num, DnSta & Num=  ,266.48, 2 ,266.48, 2 , 0 , 0 , 0 ,,
      .8      .8
   41.08   53.98
      .8      .8
   41.08   53.98
BR Coef=-1 , 0 , 0 ,, 0 ,,,.8,0,,0,
WSPro=,,,, 1 ,,,, 0 ,,,, 0 ,,,,-1 ,-1 ,-1 , 0 , 0 , 0 , 0 , 0
BC Design=,, 0 ,, 0 ,,,,,,

Type RM Length L Ch R = 1 ,3664    ,43,39,38
BEGIN DESCRIPTION:
copy of 483s2u, xs 2/4 Lk Houston GC Hole #9
Notes: Lowered elevations between main channel banks by 0.9 ft.   Also lowered left CB elevation from 57.13' to 52.25' to indicate piers/adbutment. Adjusted contraction coefficient to 0.3 and expansion coefficient to 0.5.  Adjusted Manning's n value to reflect bridge opening.
END DESCRIPTION:
XS GIS Cut Line= 6
     3205625.633    13956022.416      3205544.14     13956161.56
       3205480.1    13956236.782     3205429.275    13956302.854
     3205378.376    13956390.123      3205280.41    13956690.826
#Sta/Elev= 30
       0   61.61   22.94   61.47   46.34   59.82    66.4   59.07   99.87   59.63
  132.91   56.97  176.21   52.81     182   52.25  192.39   48.24  196.34   44.82
  197.67   43.09  204.62   40.19  211.59    43.1  212.08   44.87     221   48.69
  229.01   47.58  253.37   49.05  275.81   52.38  305.78   56.56  364.99   60.07
  394.17   61.09  457.97   63.76  475.25   64.11  526.59   64.38  610.15   64.62
  679.65   63.57  682.49   63.58  686.81   63.44  716.81   63.51  760.87   63.42
#Mann= 3 ,-1 , 0
       0     .12       0  176.21     .06       0  275.81     .12       0
#XS Ineff= 2 , 0
       0  174.21   54.52  277.81       0   54.52
Permanent Ineff=
       F       F
Bank Sta=182,221
XS Rating Curve= 0
Exp/Cntr=.5,.3

Type RM Length L Ch R = 1 ,3625    ,376,367,364
BEGIN DESCRIPTION:
copy of 483s2u, xs 1/4 Lk Houston GC Hole #9
Notes: Lowered elevations between main channel banks by 0.9 ft.  Also lowered CB elevations by 0.9 ft. Inserted block at sta 0 to 664.03 @ elev. 64.5.  T
END DESCRIPTION:
XS GIS Cut Line= 6
     3205585.263    13956007.997      3205494.14     13956161.56
       3205430.1    13956236.782     3205379.275    13956302.854
     3205328.376    13956390.123     3205230.967    13956717.706
#Sta/Elev= 30
       0   60.62   23.33   59.91   51.26   58.51   83.69    57.3   89.39   57.39
  118.34   55.13  122.25   56.97     171   56.23     182   48.24  185.68   44.82
  187.01   43.09  193.96   40.19  200.93    43.1  201.42   44.87     210   48.69
  218.35   47.58  242.71   49.05   266.6   52.59  295.12   56.56   358.5   60.37
  405.67   62.39     474   63.69   588.9   64.32   622.4   63.92  664.03    64.5
  726.09   62.32  737.55   62.17   757.8    62.8  783.23   63.16   803.7   62.56
#Mann= 3 ,-1 , 0
       0     .12       0     182     .06       0     210     .12       0
#Block Obstruct= 2 , 0
       0       0    64.5  664.03       0    64.5
Bank Sta=182,210
XS Rating Curve= 0
Exp/Cntr=.3,.1

Type RM Length L Ch R = 1 ,3259    ,50,49,50
BEGIN DESCRIPTION:
483s1u, xs 4/4 Aftonway Rd
Adjusted contraction coefficient to 0.3 and expansion coefficient to 0.5
END DESCRIPTION:
XS GIS Cut Line= 6
     3205364.694    13955552.677     3205208.914    13955958.932
     3205183.087    13955999.138      3205163.65    13956027.894
     3205130.101    13956079.283     3204887.293    13956825.744
#Sta/Elev= 30
       0   66.51   63.19   64.69   93.99   64.54  123.24   63.99   157.6   63.88
   197.7   61.86  215.97    62.2  226.25   62.05  252.26   61.17   404.5   54.63
  433.77   53.11     466   50.99  477.35   45.92   485.1   42.03  490.02   41.42
  497.06   41.68  497.48   42.84  500.55   45.52     517   51.69  630.32   54.95
  671.81   56.88  726.96   57.64  806.84   58.24  927.44   59.76 1030.05   59.86
 1054.44   59.66 1097.86   58.56 1225.42   59.49 1290.08   58.01 1363.92    58.3
#Mann= 3 , 0 , 0
       0     .12       0     466     .06       0     517     .12       0
Bank Sta=466,517
XS Rating Curve= 0
Exp/Cntr=.5,.3