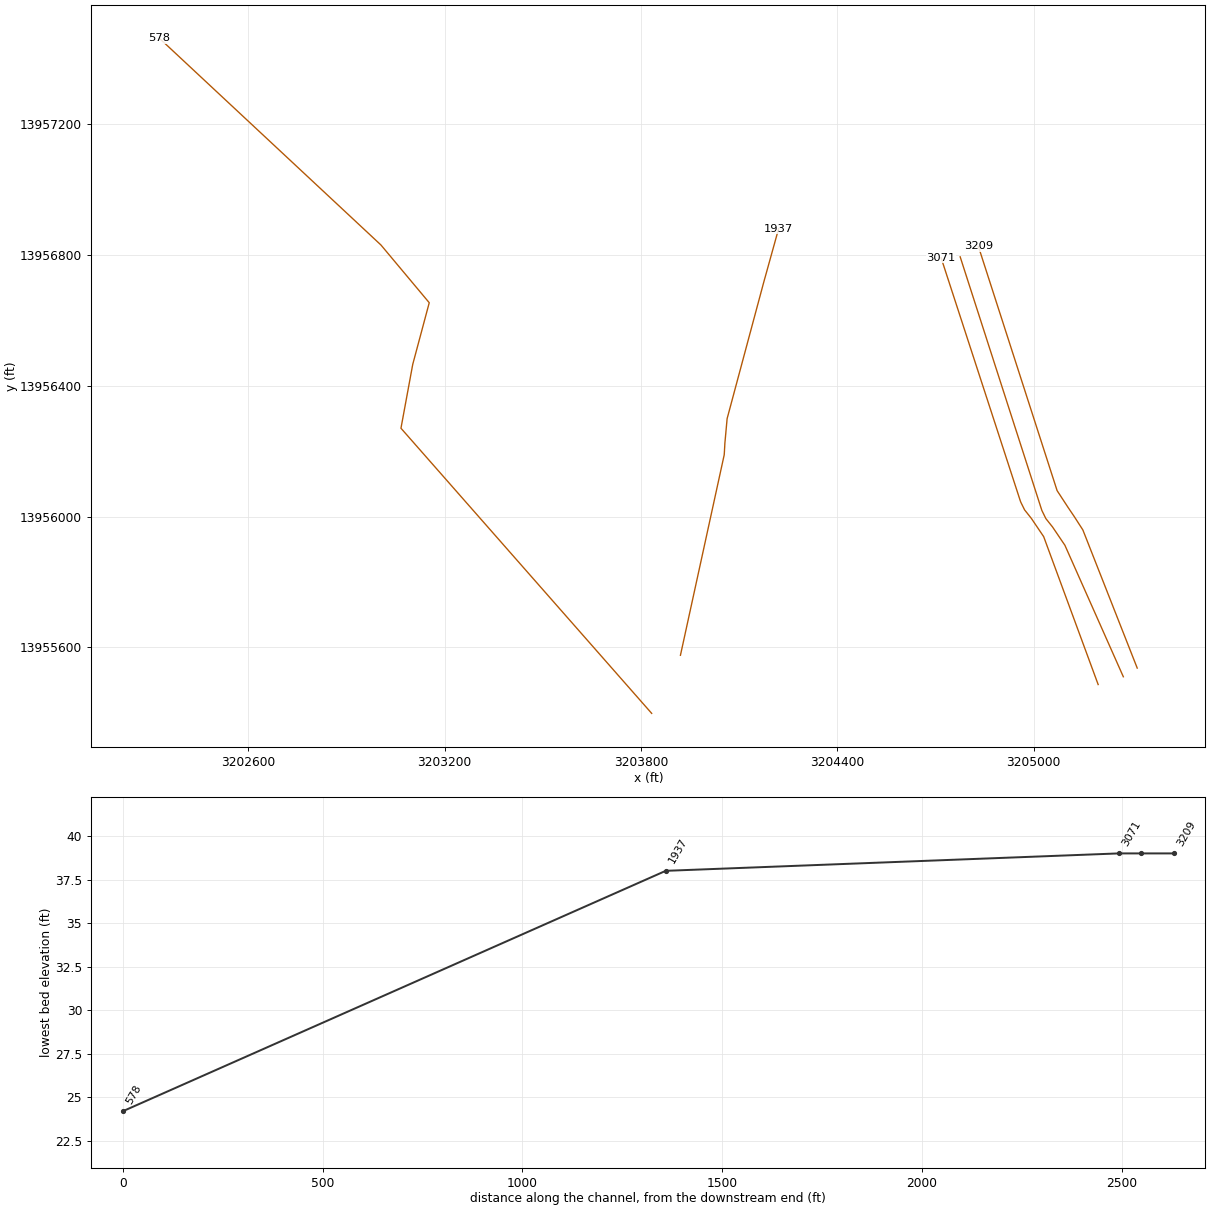
HEC-RAS study S110-00-00.prj: S110-00-00

--- S110-00-00.g02 (geometry) --- (continued)

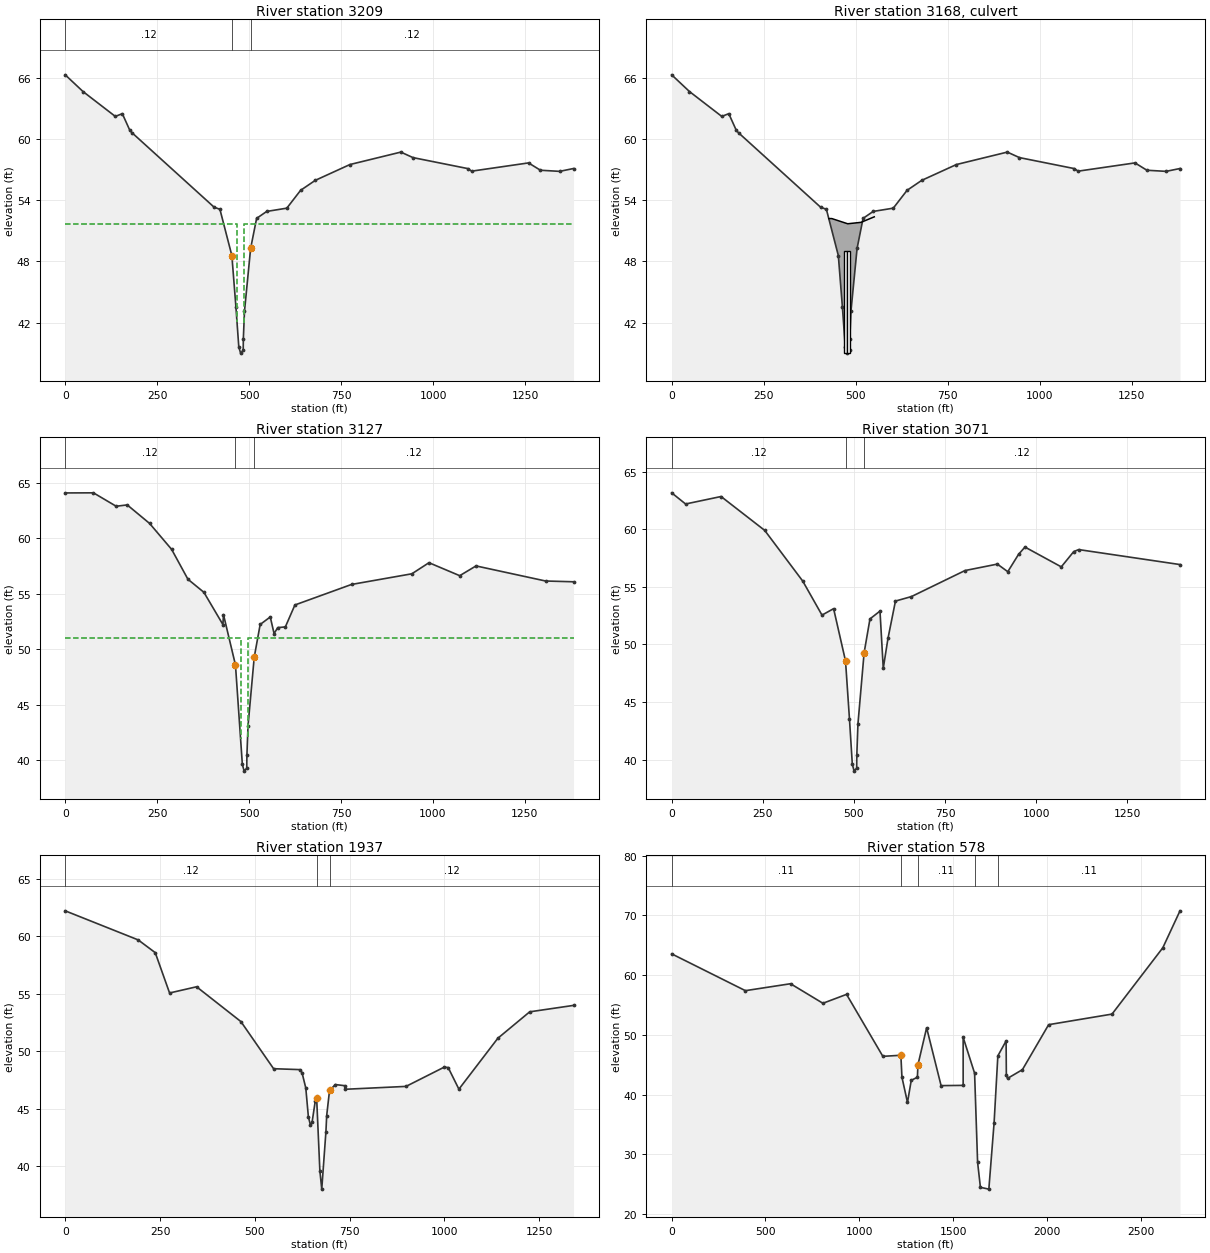
Type RM Length L Ch R = 1 ,3209    ,74,82,90
BEGIN DESCRIPTION:
copy of 483s1u, xs 3/4 Aftonway Rd
Notes:  Lowered Elev. at and between CB's by 2.42 ft based on known elevation for upstream invert of box culverts(483s1c) and x-sec survey data at RS 3259(483s1u). Adjusted contraction coefficient to 0.3 and expansion coefficient to 0.5
END DESCRIPTION:
XS GIS Cut Line= 6
     3205316.954    13955536.763     3205150.914    13955958.932
     3205125.087    13955999.138      3205105.65    13956027.894
     3205072.101    13956079.283     3204831.597    13956825.744
#Sta/Elev= 30
       0    66.3   48.41   64.66  136.21   62.22  155.22   62.49  175.86   60.84
  182.16    60.6  404.96   53.31  420.53   53.11     453   48.57  464.11    43.5
  471.86   39.61  476.78      39  483.82   39.26  484.24   40.42  487.31    43.1
     504   49.27  520.31   52.22  547.78    52.9  602.37   53.22  639.85   54.97
  679.84   55.95  773.99    57.5  912.33   58.72  945.34   58.18 1094.77    57.1
  1104.8   56.85 1259.42   57.66 1291.82   56.94    1344   56.83 1381.76   57.11
#Mann= 3 , 0 , 0
       0     .12       0     453     .06       0     504     .12       0
#XS Ineff= 2 , 0
       0     467   51.69     486       0   51.69
Permanent Ineff=
       F       F
Bank Sta=453,504
XS Rating Curve= 0
Exp/Cntr=.5,.3

Type RM Length L Ch R = 2 ,3168    ,,,
BEGIN DESCRIPTION:
483s1: Afton Way 2- 8'x10' Concrete Box Culverts
Notes: Aligned box culverts in channel based on survey notes from 483s1c and low point shown in plot at Upstream and Downstream x-sec.  Lowered CB's by 2.42 ft. Set ineffective flow at bounding river stations @ elev. 51.69'
END DESCRIPTION:
Bridge Culvert--1,0,-1,-1, 0
Deck Dist Width WeirC Skew NumUp NumDn MinLoCord MaxHiCord MaxSubmerge Is_Ogee
20.5,41,2.6,0, 5, 5, 51.69, , .95, 0, 0,0,,
     427  435.29  478.46  514.66  550.76
    52.2    52.2   51.69   51.83   52.37
                                        
     427  435.29  478.46  514.66  550.76
    52.2    52.2   51.69   51.83   52.37
                                        
BR Coef=-1 , 0 , 0 ,, 0 ,,,.8,0,,0,
WSPro=,,,, 1 ,,,, 0 ,,,, 0 ,,,,-1 ,-1 ,-1 , 0 , 0 , 0 , 0 , 0
Multiple Barrel Culv=2,10,8,61,.012,.4,1,8,1,39,38.98, 2,Afton Way RD, 0 ,10.5
  472.43  482.28  481.13  490.98
Culvert Bottom n=.012
BC Design=,, 0 ,, 0 ,,,,,,

Type RM Length L Ch R = 1 ,3127    ,48,56,51
BEGIN DESCRIPTION:
copy of 483s1u, xs 2/4 Aftonway Rd
Notes:  Lowered Elev. at and between CB's by 2.42 ft based on known elevation for upstream invert of box culverts(483s1c) and x-sec survey data at RS 3259(483s1u). Adjusted contraction coefficient to 0.3 and expansion coefficient to 0.5.
END DESCRIPTION:
XS GIS Cut Line= 6
     3205274.518    13955510.241     3205096.071     13955912.01
     3205058.467     13955967.71     3205037.676    13955993.891
     3205025.484    13956018.789       3204775.9    13956793.918
#Sta/Elev= 30
       0   64.08   76.77   64.09  138.57   62.88  168.69      63   229.5   61.33
  289.43   58.99  333.72    56.3  377.17   55.12  428.92   52.21  430.38   53.11
     463   48.57  481.71   39.61  486.63      39  493.67   39.26  494.09   40.42
  497.16    43.1     514   49.27  530.16   52.22  557.63    52.9  567.98    51.4
  577.99   51.94  598.63      52  624.62   53.98  778.65   55.83  942.64   56.79
  989.21   57.79  1072.8   56.62 1117.19    57.5 1306.38   56.14  1382.3   56.07
#Mann= 3 ,-1 , 0
       0     .12       0     463     .06       0     514     .12       0
#XS Ineff= 2 , 0
       0     477   51.01     496       0   51.01
Permanent Ineff=
       F       F
Bank Sta=463,514
XS Rating Curve= 0
Exp/Cntr=.5,.3

Type RM Length L Ch R = 1 ,3071    ,1145,1134,1259
BEGIN DESCRIPTION:
copy of 483s1u, xs 1/4 Aftonway Rd
Notes:  Lowered Elev. at and between between CB's by 2.42 ft based on known elevation for upstream invert of box culverts(483s1c) and x-sec survey data at RS 3259(483s1u).
END DESCRIPTION:
XS GIS Cut Line= 6
     3205197.604    13955486.371     3205031.071    13955938.601
     3204993.467    13955994.301     3204972.676    13956020.482
     3204960.484     13956045.38     3204717.551    13956791.265
#Sta/Elev= 30
       0   63.17   38.17    62.2  135.51   62.85   255.2   59.91  359.72    55.5
  412.47   52.55  444.31   53.11     477   48.57  487.89    43.5  495.64   39.61
  500.56      39   507.6   39.26  508.02   40.42  511.09    43.1     528   49.27
  544.09   52.22  571.56    52.9  580.56   47.93  593.46   50.52  614.02   53.77
  657.89   54.16  804.82   56.42  893.55   56.98  922.24   56.32  951.84   57.83
  969.39   58.46    1069   56.74 1103.27   58.07 1116.91   58.24 1394.74   56.94
#Mann= 3 ,-1 , 0
       0     .12       0     477     .06       0     528     .12       0
Bank Sta=477,528
XS Rating Curve= 0
Exp/Cntr=.3,.1

Type RM Length L Ch R = 1 ,1937    ,1300,1359,1199
BEGIN DESCRIPTION:
483v4
END DESCRIPTION:
XS GIS Cut Line= 6
     3203921.016    13955575.931     3204054.832     13956188.91
     3204056.918    13956225.166     3204063.656    13956299.283
     3204175.602    13956716.411     3204221.198    13956880.426
#Sta/Elev= 30
       0   62.22  192.37   59.69  237.38   58.58  275.19   55.07  346.37   55.61
   463.3   52.58  549.46   48.48  619.24    48.4  624.53   48.12  634.34    46.8
  641.14    44.3  646.34    43.6  650.84    43.8  659.44    45.7     663    45.9
  671.44    39.6  676.44      38  687.44   43.01  689.44    44.4     697    46.6
  712.44    47.1  737.44      47  738.16   46.69  898.61   46.94  999.51   48.62
 1009.78   48.58 1038.05    46.7 1140.71   51.13 1224.68   53.43 1340.28   53.99
#Mann= 3 , 0 , 0
       0     .12       0     663     .06       0     697     .12       0
Bank Sta=663,697
XS Rating Curve= 0
Exp/Cntr=.3,.1

Type RM Length L Ch R = 1 ,578     ,701,578,557
BEGIN DESCRIPTION:
483v5 Shook Gully channel Left & 481v22 Luce Bayou Right.  These 2 channel sections must be identical in the 2 models, including banks and manning's "n" except over blocked portion.  Inserted block right of station 1554 @ elevation 49.6 to confine flows within Shook Gully watershed - Luce Bayou channel will convey Luce Bayou flows.  Shook and Luce drainage areas are dissimilar and coincident peaks are not modeled.
END DESCRIPTION:
XS GIS Cut Line= 6
     3203833.115    13955398.283     3203066.919    13956269.959
     3203102.868    13956465.111     3203153.341    13956653.655
     3203005.714    13956830.179     3202328.956    13957461.915
#Sta/Elev= 30
       0   63.57  393.06   57.41  633.75   58.57  806.35    55.3  932.32   56.79
 1125.89   46.42    1222    46.6 1227.66   42.93 1257.26    38.7 1277.26    42.4
 1310.06   42.93    1313      45 1359.26    51.2 1436.36   41.52    1554   41.56
    1554    49.6    1615    43.6    1631    28.7    1646    24.5    1691    24.2
    1719    35.3    1739    46.5    1783      49 1784.33   43.27 1790.62   42.73
 1869.98   44.19 2009.85   51.72 2347.71   53.49 2618.54   64.59 2710.12   70.77
#Mann= 5 ,-1 , 0
       0     .11       0    1222     .06       0    1313     .11       0
    1615     .06       0    1739     .11       0
#Block Obstruct= 2 , 0
       0                    1554       0    49.6
Bank Sta=1222,1313
XS Rating Curve= 0
Exp/Cntr=.3,.1

Chan Stop Cuts=-1